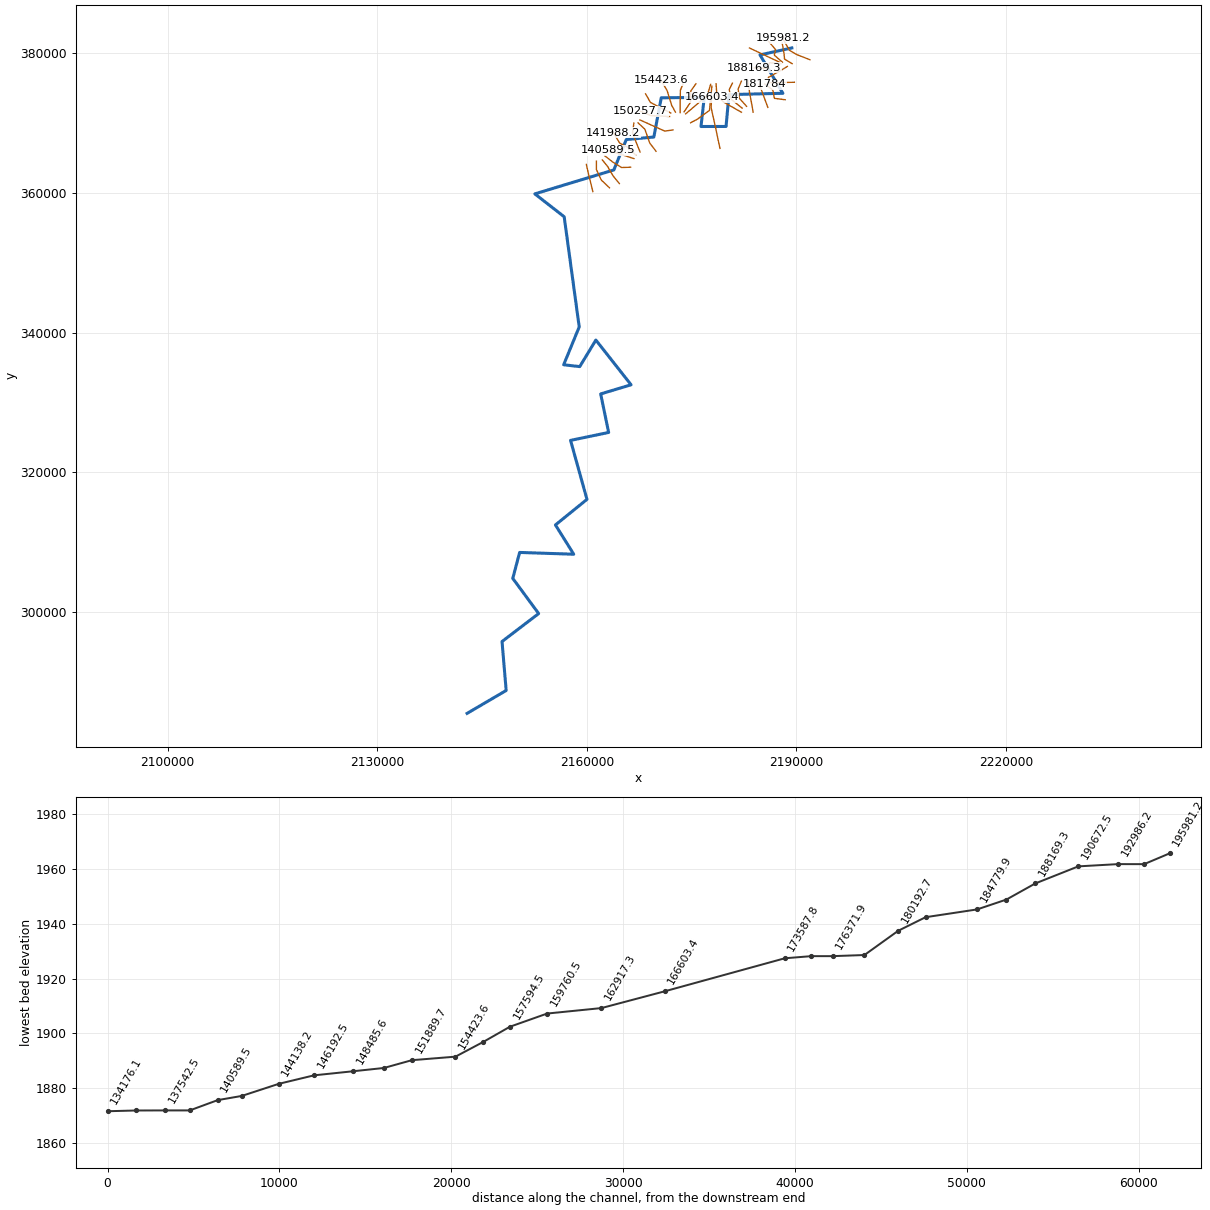
--- GrnbrRv.prj (project) ---

Proj Title=GrnbrRv
Current Plan=p01
Geom File=g01
Flow File=f01
Plan File=p01
DSS Export Rating Curves=0
DSS Export Rating Curve Sorted=0
DSS Export Volume Flow Curves=0
DXF OffsetX=0
DXF OffsetY=0
DXF ScaleX=0
DXF ScaleY=0

--- GrnbrRv.p01 (plan) ---

Plan Title=Floodplain
Program Version=4.00
Geom File=g01
Flow File=f01
K Sum by GR=0
Std Step Tol=0.01
Critical Tol=0.01
Num of Std Step Trials=20
Max Error Tol=0.3
Flow Tol Ratio=0.001
Split Flow NTrial=30
Split Flow Tol=0.02
Split Flow Ratio=0.02
Log Output Level=0
Friction Slope Method=1
Unsteady Friction Slope Method=2
Unsteady Bridges Friction Slope Method=1
Global Log Level=0
CheckData=False
Run HTab=0
Run UNet=0
Run PostProcess=0
UNET Theta=0
UNET Theta Warmup=0
UNET ZTol=0
UNET ZSATol=0
UNET MxIter=0
UNET MaxInSteps=0
UNET DtIC=0
UNET DtMin=0
UNET MaxCRTS=0
UNET WFStab=0
UNET SFStab=0
UNET WFX=0
UNET SFX=0
UNET DSS MLevel=0
UNET DZMax Abort=0
UNET Convert EG Bridges=0
UNET Use Existing IB Tables=0
UNET Froude Limit=0
UNET Froude Power=0
Write IC File=0
Echo Input=False
Echo Output=False
Write Detailed=0

--- GrnbrRv.f01 (steady flow) ---

Flow Title=NFF Regression Equation
Program Version=4.00
Number of Profiles=1
Profile Names=P100yr
River Rch & RM=GrnbrRv,Main      ,195981.2
53115.18
River Rch & RM=GrnbrRv,Main      ,137542.5
55060.73
River Rch & RM=GrnbrRv,Main      ,110306.2
55629.86
River Rch & RM=GrnbrRv,Main      ,109372.6
62657.67
River Rch & RM=GrnbrRv,Main      ,75537.3
63840.05
River Rch & RM=GrnbrRv,Main      ,68910.3
63868.59
River Rch & RM=GrnbrRv,Main      ,67772.8
72906.78
River Rch & RM=GrnbrRv,Main      ,42427.4
73631.00
River Rch & RM=GrnbrRv,Main      ,10353.8
17.96609
River Rch & RM=GrnbrRv,Main      ,9970.899
17.96609
River Rch & RM=GrnbrRv,Main      ,8999
71.96405
River Rch & RM=GrnbrRv,Main      ,5858.8
31.28077
River Rch & RM=GrnbrRv,Main      ,5568.2
74526.62
Boundary for River Rch & Prof#=GrnbrRv,Main            , 1
Up Type= 0
Dn Type= 1
Dn Known WS=1691

--- GrnbrRv.g01 (geometry) ---

Geom Title=USGS 10m DEM
Program Version=4.10

River Reach=GrnbrRv         ,Main
Reach XY= 30
     2189344.415      380729.665      2184787.83      379736.384
     2188065.608      374241.592     2180352.066       374050.62
     2179931.927      369493.329     2176347.422      369486.735
     2176808.663      373654.787     2170657.622      373595.759
     2169598.594       367979.44      2165654.15      367620.065
       2163872.9       363269.37     2152565.495      359844.395
     2156765.148       356570.09     2158916.129      340799.014
      2156692.17      335385.819     2158992.518      335123.666
     2161301.545      338922.278     2166338.004      332521.236
     2161989.045      331210.472     2163127.934      325698.319
     2157678.281      324564.639      2160027.24       316121.93
     2155513.351      312462.208      2158129.67      308271.236
     2150390.087      308526.444     2149409.184      304811.166
     2153112.309      299776.444     2147869.253       295778.18
     2148463.004        288769.5     2142870.169      285493.912

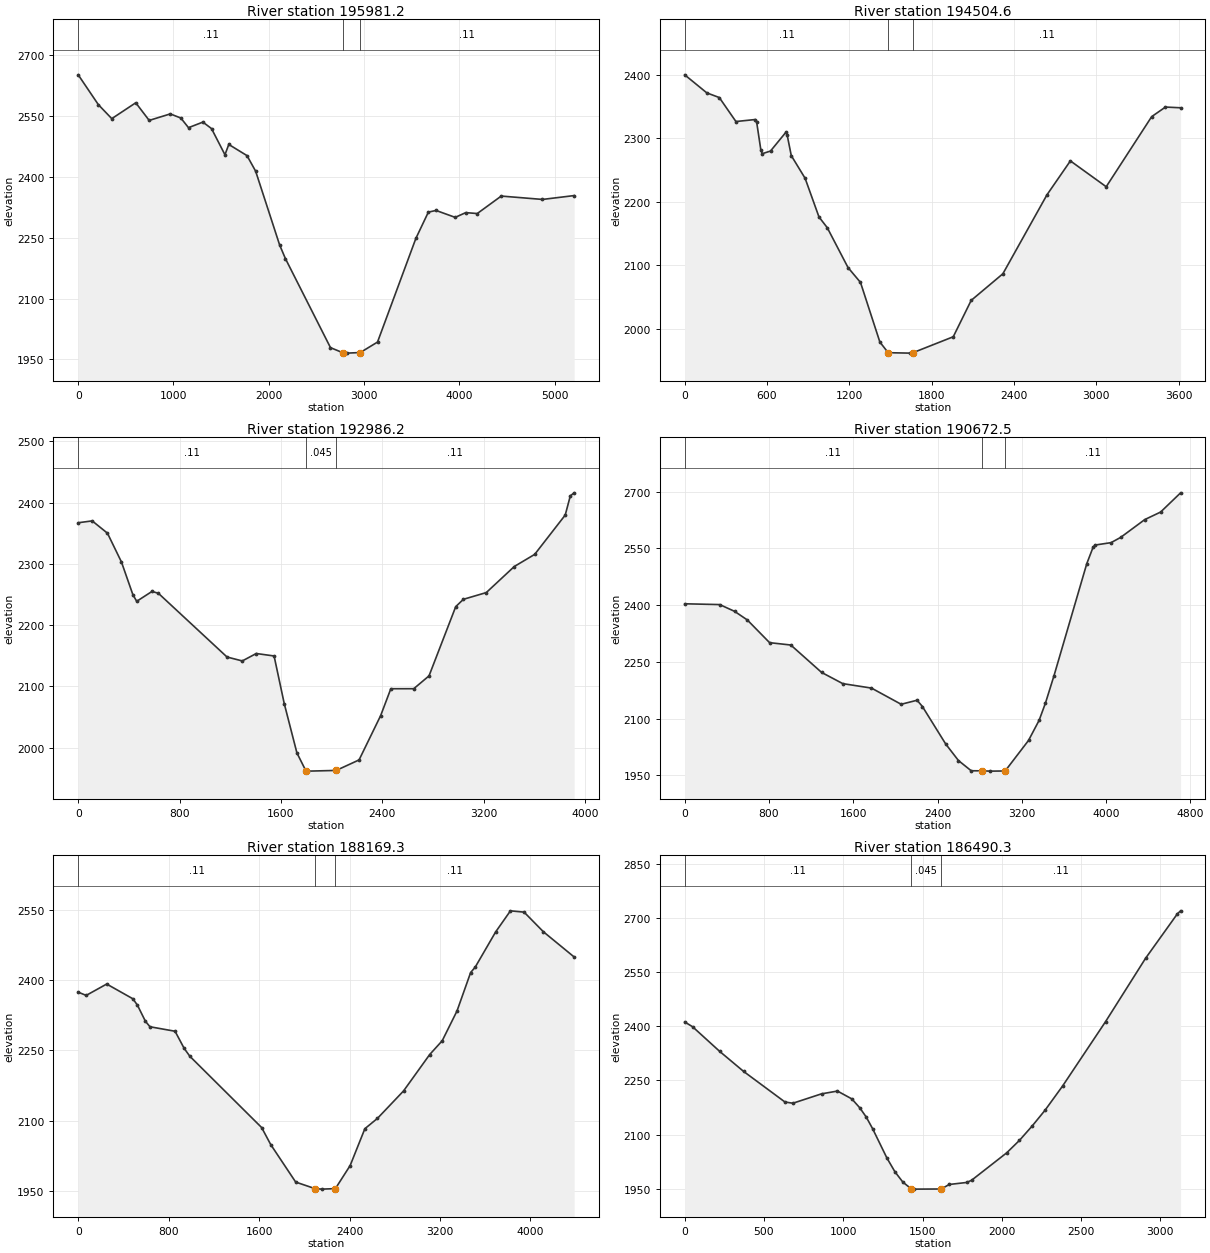
Type RM Length L Ch R = 1 ,195981.2,1497.8,1476.6,1455.6
XS GIS Cut Line= 4
     2191939.236      379045.648     2190070.593      379768.189
     2188994.284      380402.459      2188037.51      382105.238
#Sta/Elev= 30
       0 2650.94   211.4 2577.52   352.4 2543.02   604.1 2582.11     745 2538.68
   966.5  2554.7  1077.2 2544.56  1157.8  2520.8  1308.8 2534.53  1399.4 2518.53
  1540.4 2454.07  1580.6 2479.49  1771.9 2451.96  1862.5 2413.68  2114.3    2232
  2174.7 2198.52  2648.3 1979.06  2779.2 1966.45  2819.5 1965.57  2960.6 1966.99
  3141.9 1992.78  3544.7 2248.18  3675.6  2312.8  3756.2 2316.96  3957.5  2299.9
  4068.3 2311.58  4189.1 2309.33  4440.8 2352.37  4873.7 2344.07  5205.9 2353.56
#Mann= 3 , 0 , 0
       0     .11       0  2779.2    .045       0  2960.6     .11       0
Bank Sta=2779.2,2960.6
XS Rating Curve= 0 ,0
Exp/Cntr=0.3,0.1

Type RM Length L Ch R = 1 ,194504.6,1524.9,1518.3,1511.8
XS GIS Cut Line= 4
     2189395.219      378476.015     2188299.982      379140.981
     2188241.308      379845.062     2187967.499      381448.801
#Sta/Elev= 30
       0 2399.76   161.4 2371.32   252.2    2364   373.3 2326.24   514.5  2329.4
   524.6 2325.22   554.9 2281.69     565 2275.58   625.5  2279.8   736.5 2309.07
   746.6  2305.3   776.8 2272.62   877.7 2236.86   978.6 2176.11  1039.2 2159.09
  1190.5 2096.35  1281.3 2072.99  1422.6 1979.13  1483.2 1962.33  1644.6 1961.66
  1664.8 1962.42  1957.5 1987.42  2088.2 2044.68  2319.2 2086.57  2640.6 2210.87
  2811.3 2264.27  3072.4 2223.59  3403.9 2333.95  3504.3 2349.02  3614.8 2347.88
#Mann= 3 , 0 , 0
       0     .11       0  1483.2    .045       0  1664.8     .11       0
Bank Sta=1483.2,1664.8
XS Rating Curve= 0 ,0
Exp/Cntr=0.3,0.1

Type RM Length L Ch R = 1 ,192986.2,2283.6,2313.7,2343.9
XS GIS Cut Line= 4
     2188006.615      378681.372     2186842.925      379698.378
     2187015.986      380500.697     2186014.289      381679.299
#Sta/Elev= 30
       0 2367.07   110.4 2370.09   230.8 2350.01   341.2    2303   431.5 2249.57
   461.6 2238.84   582.1 2254.94   632.2 2251.99  1174.2 2147.91  1294.6 2141.51
    1405 2153.64  1545.5 2149.62  1625.5 2072.04  1725.6 1991.43  1795.7 1962.41
  1815.7 1961.67  2035.9 1962.81  2216.1 1979.97  2386.3 2052.25  2466.7 2096.17
  2647.5 2096.19    2768 2117.13  2978.9 2230.18  3039.2 2242.09    3220 2253.11
  3440.9 2295.64  3601.6 2315.42  3842.7  2379.6  3882.9 2410.93    3913  2415.9
#Mann= 3 , 0 , 0
       0     .11       0  1795.7    .045       0  2035.9     .11       0
Bank Sta=1795.7,2035.9
XS Rating Curve= 0 ,0
Exp/Cntr=0.3,0.1

Type RM Length L Ch R = 1 ,190672.5,2466.5,2503.2,2539.7
XS GIS Cut Line= 3
     2187535.745      378713.751     2184175.696      380300.661
     2183280.827      380725.166
#Sta/Elev= 30
       0 2403.34   332.3 2401.21   473.3 2383.37   594.2 2360.58   805.6 2300.56
    1007  2294.3  1299.1 2221.86  1500.5  2192.2  1772.4 2180.45  2054.3  2137.6
  2205.4 2148.29  2255.8 2131.73  2477.3 2032.47  2598.1 1988.83    2719 1961.81
  2819.7 1961.63  2900.2 1960.85  3041.2 1961.26  3262.8 2041.93  3363.5 2095.18
  3423.9 2140.99  3504.5 2212.92    3816 2509.56    3876 2553.07    3896  2558.7
  4046.1 2565.01  4136.1 2578.65  4366.2 2626.01  4516.3 2645.87  4706.4 2696.74
#Mann= 3 , 0 , 0
       0     .11       0  2819.7    .045       0  3041.2     .11       0
Bank Sta=2819.7,3041.2
XS Rating Curve= 0 ,0
Exp/Cntr=0.3,0.1

Type RM Length L Ch R = 1 ,188169.3,1694.1,1679,1664.1
XS GIS Cut Line= 4
     2187776.427      378473.068     2186160.418      378619.197
      2185807.99      377776.809     2183959.895      377879.959
#Sta/Elev= 30
       0 2374.19    70.6 2367.31     252 2391.52   483.8 2360.08   524.1  2346.4
   594.6 2312.15   634.9 2300.49   856.6 2290.96   937.3 2254.45   987.7 2237.58
  1622.6 2085.79  1702.9 2049.54  1923.6 1969.68  2094.2 1955.74  2154.4 1954.63
  2274.8 1955.69  2405.3 2004.79  2535.7 2083.38  2646.4 2105.22  2877.8  2163.8
  3109.1 2241.34  3219.8  2270.7  3350.6 2334.12  3471.3 2416.08  3511.5 2427.45
  3692.6 2502.59  3823.4 2547.48  3944.1  2544.7  4115.1 2502.82  4386.7 2449.19
#Mann= 3 , 0 , 0
       0     .11       0  2094.2    .045       0  2274.8     .11       0
Bank Sta=2094.2,2274.8
XS Rating Curve= 0 ,0
Exp/Cntr=0.3,0.1

Type RM Length L Ch R = 1 ,186490.3,1721.4,1710.4,1700.1
XS GIS Cut Line= 4
     2188704.773      378077.662     2187905.364      377596.297
      2186994.21       377080.55     2185997.098      376513.227
#Sta/Elev= 30
       0 2411.68    50.2 2398.15   220.7 2330.09   371.2 2274.76   632.1 2189.99
   682.3 2186.59   862.9 2212.58   963.4 2220.25    1054 2198.58  1104.3 2173.81
  1144.6 2148.48  1184.8  2116.3  1275.4 2034.75  1325.8 1996.78  1376.1 1968.07
  1426.4 1950.44  1446.6 1948.77  1617.7 1949.16  1668.1 1961.64  1778.8 1967.26
    1809 1973.27  2030.5 2049.23    2111 2083.72  2191.5  2123.7    2272 2166.96
  2382.7 2233.98  2654.4 2412.72    2906 2587.63  3107.2 2711.12  3127.4 2719.25
#Mann= 3 , 0 , 0
       0     .11       0  1426.4    .045       0  1617.7     .11       0
Bank Sta=1426.4,1617.7
XS Rating Curve= 0 ,0
Exp/Cntr=0.3,0.1

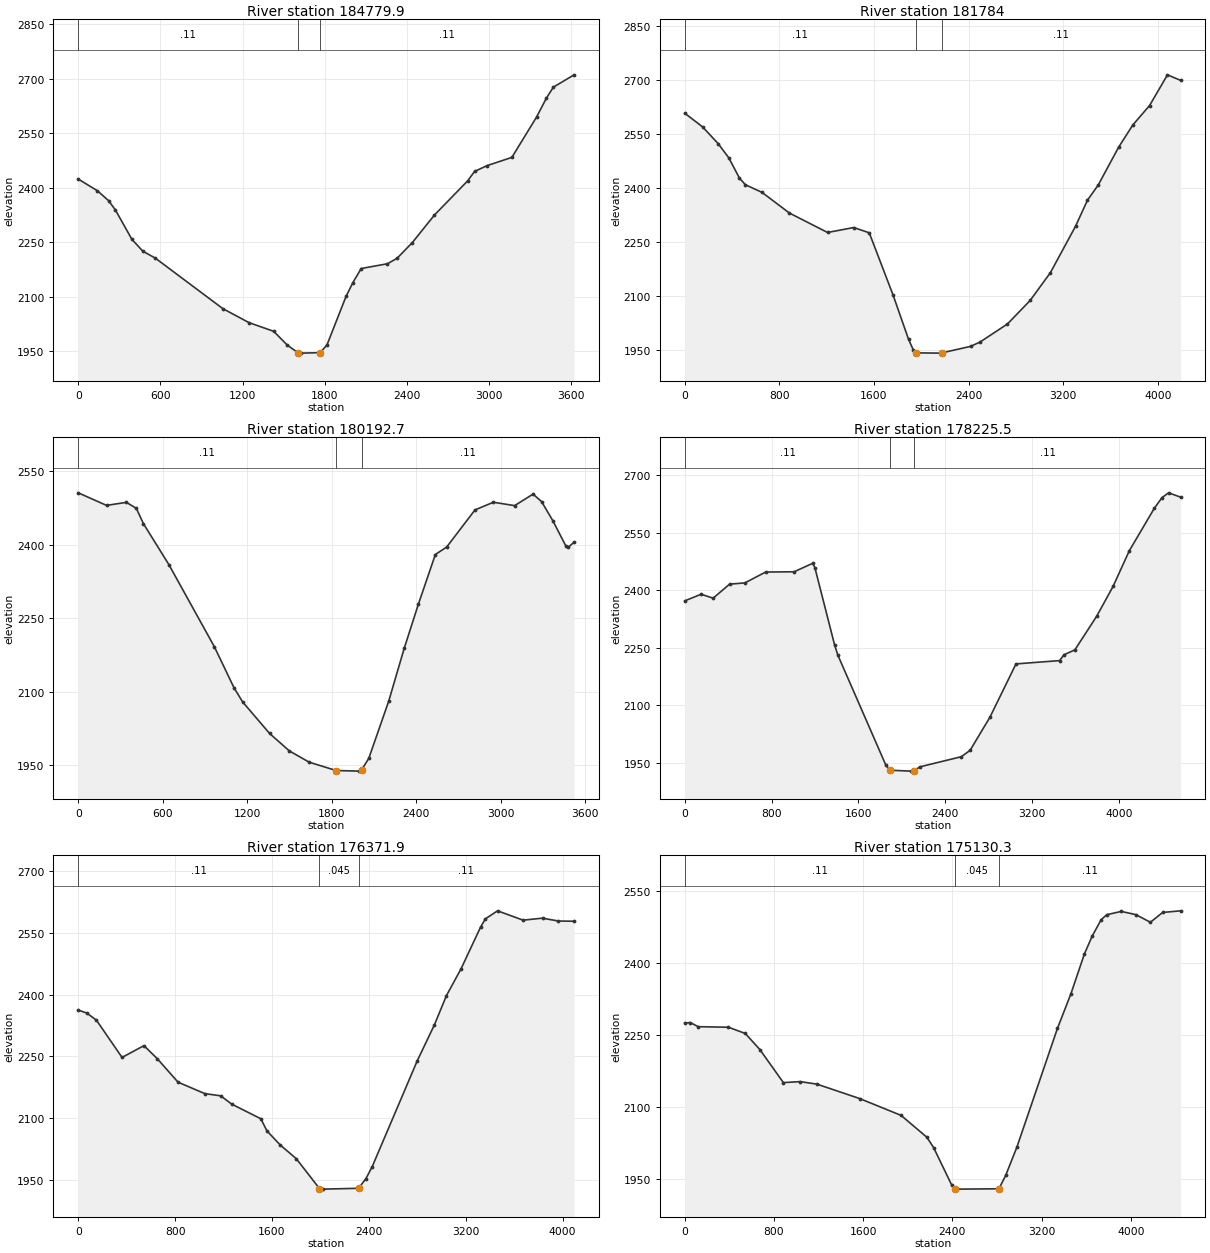
Type RM Length L Ch R = 1 ,184779.9,3027.4,2995.9,2963.6
XS GIS Cut Line= 4
     2189710.481      375816.968      2188343.75      375791.181
     2187716.257      375765.393     2186091.652      375765.393
#Sta/Elev= 30
       0 2424.05   140.7  2391.6   221.1 2364.76   271.4 2338.95     392 2258.06
   472.4 2225.28   562.9 2206.46  1055.4  2067.6  1246.4 2029.09  1426.8  2005.2
  1526.5 1967.08  1606.2 1945.63  1626.2 1945.17  1765.7 1946.42  1815.6  1967.5
  1955.1 2101.27  2005.1 2139.37  2065.6  2177.9  2257.4 2190.98    2328 2206.19
    2439  2249.3  2600.4 2325.08  2842.6 2418.97  2893.1 2444.84  2983.9 2460.81
  3165.5 2483.58  3347.2  2595.5  3417.8 2646.85  3468.2 2676.72  3619.6 2710.62
#Mann= 3 , 0 , 0
       0     .11       0  1606.2    .045       0  1765.7     .11       0
Bank Sta=1606.2,1765.7
XS Rating Curve= 0 ,0
Exp/Cntr=0.3,0.1

Type RM Length L Ch R = 1 ,181784  ,1588,1591.3,1594.6
XS GIS Cut Line= 4
      2188403.92      373315.592     2186856.677      373513.295
     2186624.591      374699.515     2185489.946      375559.094
#Sta/Elev= 30
       0 2607.22     151 2569.24   281.8 2523.14   372.3 2483.64   462.9 2427.07
   513.2 2408.92   654.1 2387.65   885.6 2330.36  1207.6 2276.66    1429 2290.37
  1559.8 2275.77  1761.3 2103.24  1892.2 1980.51  1932.5 1950.86 1952.11 1943.09
  2164.2 1942.34  2174.2 1943.13    2416 1960.96  2496.6 1973.11  2728.2 2023.14
    2920 2088.25  3091.6 2165.54  3303.6 2293.85  3404.6 2366.15  3495.4 2408.13
    3667 2512.43  3788.2 2574.66  3929.5 2628.44    4081  2713.5    4192 2698.13
#Mann= 3 , 0 , 0
       0     .11       0 1952.11    .045       0  2174.2     .11       0
Bank Sta=1952.11,2174.2
XS Rating Curve= 0 ,0
Exp/Cntr=0.3,0.1

Type RM Length L Ch R = 1 ,180192.7,1969.5,1967.2,1964.9
XS GIS Cut Line= 3
     2185911.699      372218.995     2185120.327      374372.875
     2184699.133      375524.711
#Sta/Elev= 30
       0 2505.83   201.3 2480.19   342.2 2486.36   412.6 2474.15     463 2442.88
   644.1 2359.05   966.2 2191.77  1107.1 2107.22  1167.5 2078.78  1358.7 2014.39
  1499.6  1978.6  1640.5  1955.6  1831.7 1938.66  1992.7  1937.4  2012.9 1940.26
  2063.2 1963.45  2204.1 2079.73  2314.8 2188.18  2415.3 2278.32  2535.9 2379.79
  2616.4 2395.14  2817.4 2470.93  2948.1 2486.59  3098.9  2479.7  3229.6 2503.18
  3289.9 2488.02  3370.3 2448.78  3460.8 2398.22  3480.9  2394.9  3521.1 2405.04
#Mann= 3 , 0 , 0
       0     .11       0  1831.7    .045       0  2012.9     .11       0
Bank Sta=1831.7,2012.9
XS Rating Curve= 0 ,0
Exp/Cntr=0.3,0.1

Type RM Length L Ch R = 1 ,178225.5,1856.4,1853.6,1850.8
XS GIS Cut Line= 3
     2183813.766      371536.263     2183300.571      374361.492
     2183048.741      376040.459
#Sta/Elev= 30
       0  2372.7   151.1 2390.02     262  2379.8   413.1 2416.34   554.1 2419.58
   745.6 2447.93  1007.5 2448.61  1178.8 2470.65    1199  2459.6  1380.3 2258.48
  1410.5 2231.41  1853.9 1943.76  1894.2 1930.86  2085.6 1928.57  2115.8 1930.16
  2166.2 1939.71    2549 1966.19  2629.6 1982.88    2811  2068.6  3052.3 2208.29
  3454.1 2216.92  3494.3 2232.02  3594.8 2244.94  3795.7 2332.57  3946.4 2410.25
    4097 2503.82  4328.1 2614.84  4398.4 2642.28  4458.7 2654.58  4569.2 2643.29
#Mann= 3 , 0 , 0
       0     .11       0  1894.2    .045       0  2115.8     .11       0
Bank Sta=1894.2,2115.8
XS Rating Curve= 0 ,0
Exp/Cntr=0.3,0.1

Type RM Length L Ch R = 1 ,176371.9,1239.9,1241.6,1243.2
XS GIS Cut Line= 4
     2182868.229      372378.651     2181828.138      373539.083
     2181664.818      374871.431     2182128.991      375971.692
#Sta/Elev= 30
       0 2362.41    70.4  2355.2   150.8 2337.79   361.9 2247.51   542.9 2276.13
   653.5 2244.32   824.4 2187.51  1045.6 2159.75  1176.3 2154.46  1266.8 2134.47
  1508.1 2098.78  1558.3  2069.4  1669.4 2034.85  1800.6 2002.06  1992.3 1929.56
  2022.6 1928.16  2315.3 1930.17  2375.8 1953.76  2426.3 1981.76  2799.7 2239.45
  2940.8  2326.2  3041.1 2397.71  3161.6 2462.67  3322.1 2563.35  3362.3 2583.57
  3462.6 2603.07  3673.4 2580.45  3833.9 2585.29  3964.4 2578.35  4094.8  2577.8
#Mann= 3 , 0 , 0
       0     .11       0  1992.3    .045       0  2315.3     .11       0
Bank Sta=1992.3,2315.3
XS Rating Curve= 0 ,0
Exp/Cntr=0.3,0.1

Type RM Length L Ch R = 1 ,175130.3,1528.9,1542.5,1556.1
XS GIS Cut Line= 4
     2182223.544      372120.777      2180659.11      373384.359
     2180384.045      374759.686     2180839.622      375688.031
#Sta/Elev= 30
       0 2274.07    50.3 2274.99   120.7 2266.44   392.1 2265.28     543 2252.33
   673.7 2218.88   884.8 2149.96  1035.7 2152.05  1186.5 2146.74  1568.6 2116.79
  1940.6  2081.7  2172.4  2036.1    2233 2014.34  2394.4  1936.7  2424.7  1928.7
  2444.9 1928.16  2818.2 1928.87  2878.8 1956.71  2979.7 2015.93  3342.9 2262.86
  3463.8 2334.99  3584.2 2417.57  3654.5 2455.09  3734.8 2489.18    3785 2499.61
  3915.6 2506.49  4046.1 2499.74  4176.6  2483.9    4287 2504.34  4447.7  2507.7
#Mann= 3 , 0 , 0
       0     .11       0  2424.7    .045       0  2818.2     .11       0
Bank Sta=2424.7,2818.2
XS Rating Curve= 0 ,0
Exp/Cntr=0.3,0.1

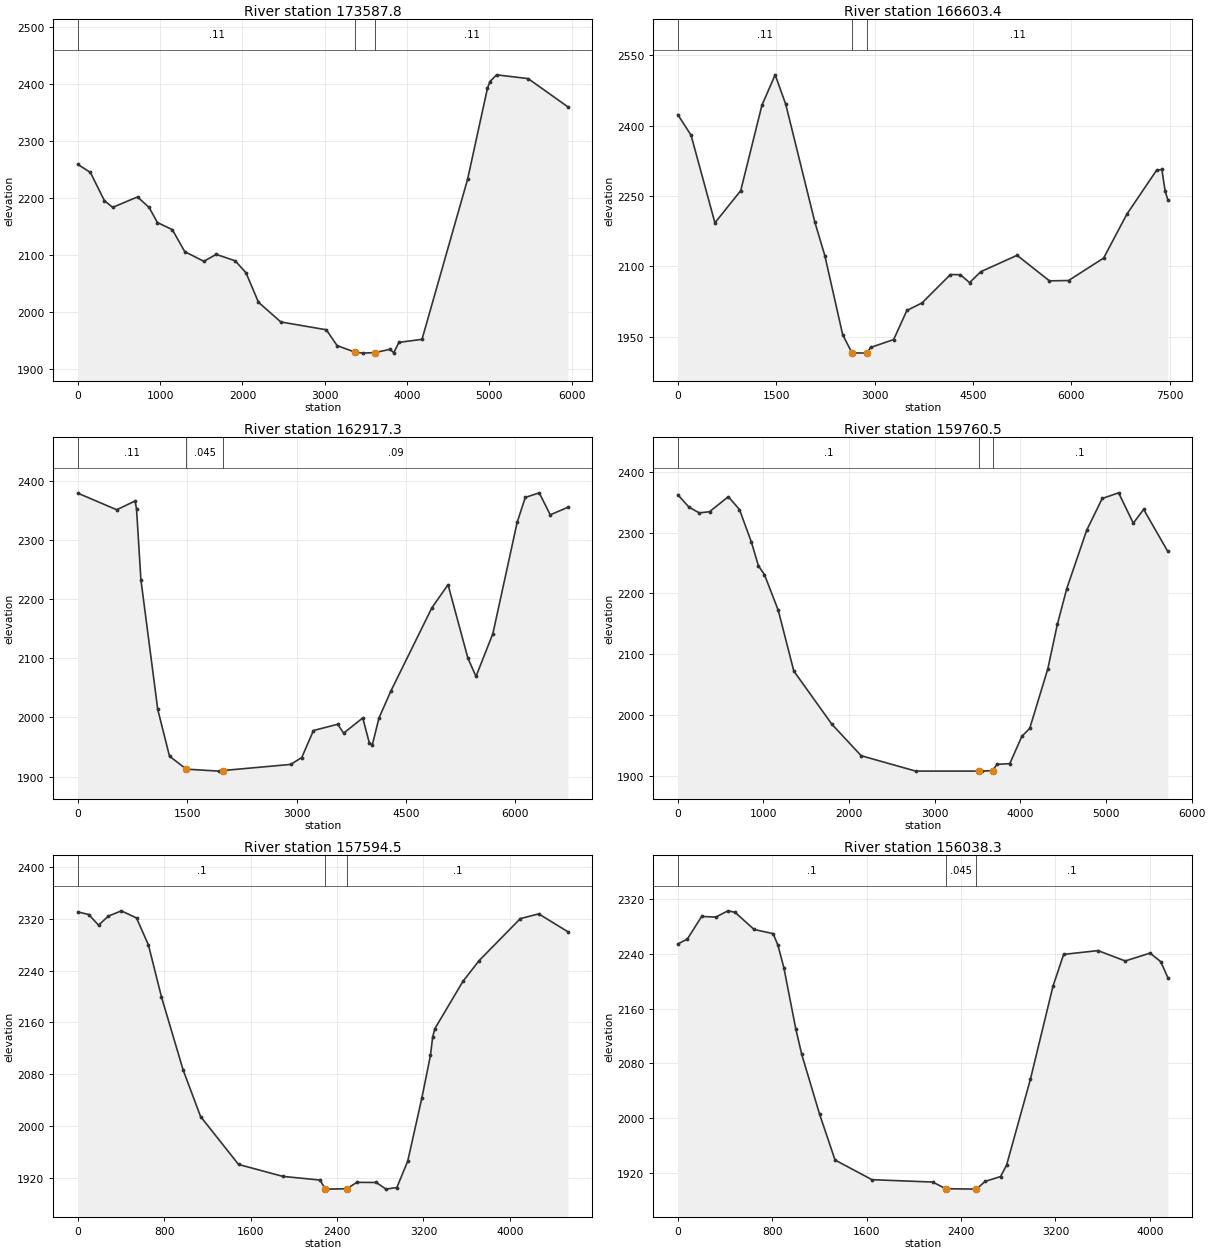
Type RM Length L Ch R = 1 ,173587.8,6997.7,6984.4,6971
XS GIS Cut Line= 4
     2182131.216      371526.692      2179603.52      372967.715
     2178623.152      373900.837     2178505.035      375589.905
#Sta/Elev= 30
       0 2258.69     151  2244.8   322.2 2195.13   422.8 2183.34   724.9 2201.68
   865.8  2183.1   966.5 2156.68  1147.7 2144.23  1298.8 2105.58  1530.3 2088.65
  1681.3  2100.8  1912.9 2089.44  2043.8 2068.26  2194.8 2016.68  2466.6  1982.1
  3019.9 1968.37  3150.2 1940.65  3370.8 1928.97 3466.05 1927.38  3611.4 1928.33
  3791.9 1934.03  3839.5 1928.13  3902.1 1946.24  4182.8 1951.61  4736.8 2232.63
  4978.6 2392.78  5008.9 2404.28  5089.5 2416.07  5472.5 2409.45  5956.2 2359.82
#Mann= 3 , 0 , 0
       0     .11       0  3370.8    .045       0  3611.4     .11       0
Bank Sta=3370.8,3611.4
XS Rating Curve= 0 ,0
Exp/Cntr=0.3,0.1

Type RM Length L Ch R = 1 ,166603.4,3703.5,3686.1,3667.6
XS GIS Cut Line= 4
     2179060.183      366353.183      2178391.23      369503.855
     2177796.335      372176.334     2177867.205      373688.227
#Sta/Elev= 30
       0 2423.19   201.9 2379.26   565.4 2192.82   959.2 2261.41  1282.3 2443.14
  1484.2 2507.94  1645.8 2445.14  2090.1 2194.02  2241.5 2123.15  2514.1 1954.55
  2655.5 1915.99  2877.6 1915.36  2887.7 1916.18  2938.2 1927.38  3291.4 1944.26
  3492.7 2006.17  3724.2 2022.29    4157 2082.68    4308 2082.32  4448.9 2065.54
    4620 2088.76  5173.7 2123.62  5666.9 2069.28  5958.8 2069.96  6493.6 2117.82
  6846.8 2211.04  7300.8 2304.71  7381.5 2306.41    7432 2259.98  7472.4 2242.22
#Mann= 3 , 0 , 0
       0     .11       0  2655.5    .045       0  2887.7     .11       0
Bank Sta=2655.5,2887.7
XS Rating Curve= 0 ,0
Exp/Cntr=0.3,0.1

Type RM Length L Ch R = 1 ,162917.3,3162.7,3156.7,3150.8
XS GIS Cut Line= 4
     2174867.026      370027.146     2175817.493      370529.078
     2177560.102       371798.36      2177902.64       375270.99
#Sta/Elev= 30
       0  2379.3   532.4 2351.32   783.5 2366.09   803.6 2353.25   863.9 2233.09
    1095 2013.54  1256.2 1934.47  1487.9 1912.58  1933.7 1909.25  1991.6 1910.28
  2918.4 1920.61  3069.5 1932.23  3230.7 1977.94  3563.5 1988.54  3644.2 1973.48
  3906.4 1999.22  3997.2 1956.88  4037.5 1953.46  4128.3 1998.84  4289.7 2044.09
  4854.4 2185.47  5076.3 2224.62  5348.6 2100.38  5459.6 2069.35  5691.5 2141.95
  6024.3 2330.08  6135.3 2372.11  6326.9 2379.94  6478.2 2342.78  6720.2 2355.48
#Mann= 3 , 0 , 0
       0     .11       0  1487.9    .045       0  1991.6     .09       0
Bank Sta=1487.9,1991.6
XS Rating Curve= 0 ,0
Exp/Cntr=0.3,0.1

Type RM Length L Ch R = 1 ,159760.5,2145.9,2166,2186.1
XS GIS Cut Line= 4
     2174151.505      371297.996     2174771.048      371819.305
     2177248.534      373935.809     2177725.465      375519.035
#Sta/Elev= 30
       0 2362.16     130 2341.81   249.9 2332.35   369.9 2334.22   589.8 2359.01
   719.7 2337.83   860.1 2283.88   940.8 2245.24  1011.4 2230.74  1172.9 2171.84
  1354.4 2071.98  1798.3 1984.51  2141.3 1932.61  2776.9 1907.32  3513.3 1907.32
  3553.6 1907.26  3674.7  1908.1  3725.2 1918.36  3876.5 1919.66  4017.7 1964.72
  4108.5 1977.43  4320.2 2075.57  4431.1 2148.62    4542 2207.83  4773.9 2303.63
  4955.4 2356.02    5147 2365.34  5318.4 2315.43  5439.3 2338.11  5721.6 2268.79
#Mann= 3 , 0 , 0
       0      .1       0  3513.3    .045       0  3674.7      .1       0
Bank Sta=3513.3,3674.7
XS Rating Curve= 0 ,0
Exp/Cntr=0.3,0.1

Type RM Length L Ch R = 1 ,157594.5,1557.3,1556.2,1555.1
XS GIS Cut Line= 4
     2173919.658      371578.908     2174843.419      372944.092
     2174883.214      374570.101     2175618.418       375596.66
#Sta/Elev= 30
       0 2330.58   100.5 2326.56     191 2310.15   281.4 2324.07     402  2332.3
   542.8 2321.23   653.3 2279.41   773.9 2199.22   974.9 2086.27  1135.8 2014.62
  1487.5 1940.58  1899.4 1922.08  2240.7  1916.5 2290.77 1903.01    2311 1902.46
  2491.7 1903.08  2582.1 1912.92  2762.8 1912.73  2853.2 1902.47  2953.6 1904.96
    3054 1945.61  3184.5 2042.79  3264.8 2109.16  3284.9 2137.18  3304.9 2150.18
  3565.5 2223.43  3715.8 2255.46  4096.6 2320.26    4267 2327.59  4537.5    2300
#Mann= 3 , 0 , 0
       0      .1       0 2290.77    .045       0  2491.7      .1       0
Bank Sta=2290.77,2491.7
XS Rating Curve= 0 ,0
Exp/Cntr=0.3,0.1

Type RM Length L Ch R = 1 ,156038.3,1607.5,1614.8,1622.1
XS GIS Cut Line= 3
     2173355.149      371479.445     2173390.584      374668.595
     2173768.557       375554.47
#Sta/Elev= 30
       0 2254.15    80.7 2261.39   201.9 2294.24     323 2293.41   423.9 2302.48
   484.5 2300.35   645.9 2275.36   807.4 2269.23   847.8 2252.63   898.3 2219.82
   999.2 2130.83  1049.7 2093.44    1201 2006.26  1332.3 1939.34  1645.1 1910.68
  2159.9 1907.22  2270.9 1897.49  2523.2 1896.91  2530.7 1896.98    2604 1908.18
  2735.2 1915.24  2785.6  1931.7  2987.5 2056.72  3179.2 2192.56  3269.6 2238.99
  3560.6 2244.51  3791.3 2229.42    4002 2240.88  4092.3 2228.39  4152.5 2205.24
#Mann= 3 , 0 , 0
       0      .1       0  2270.9    .045       0  2530.7      .1       0
Bank Sta=2270.9,2530.7
XS Rating Curve= 0 ,0
Exp/Cntr=0.3,0.1

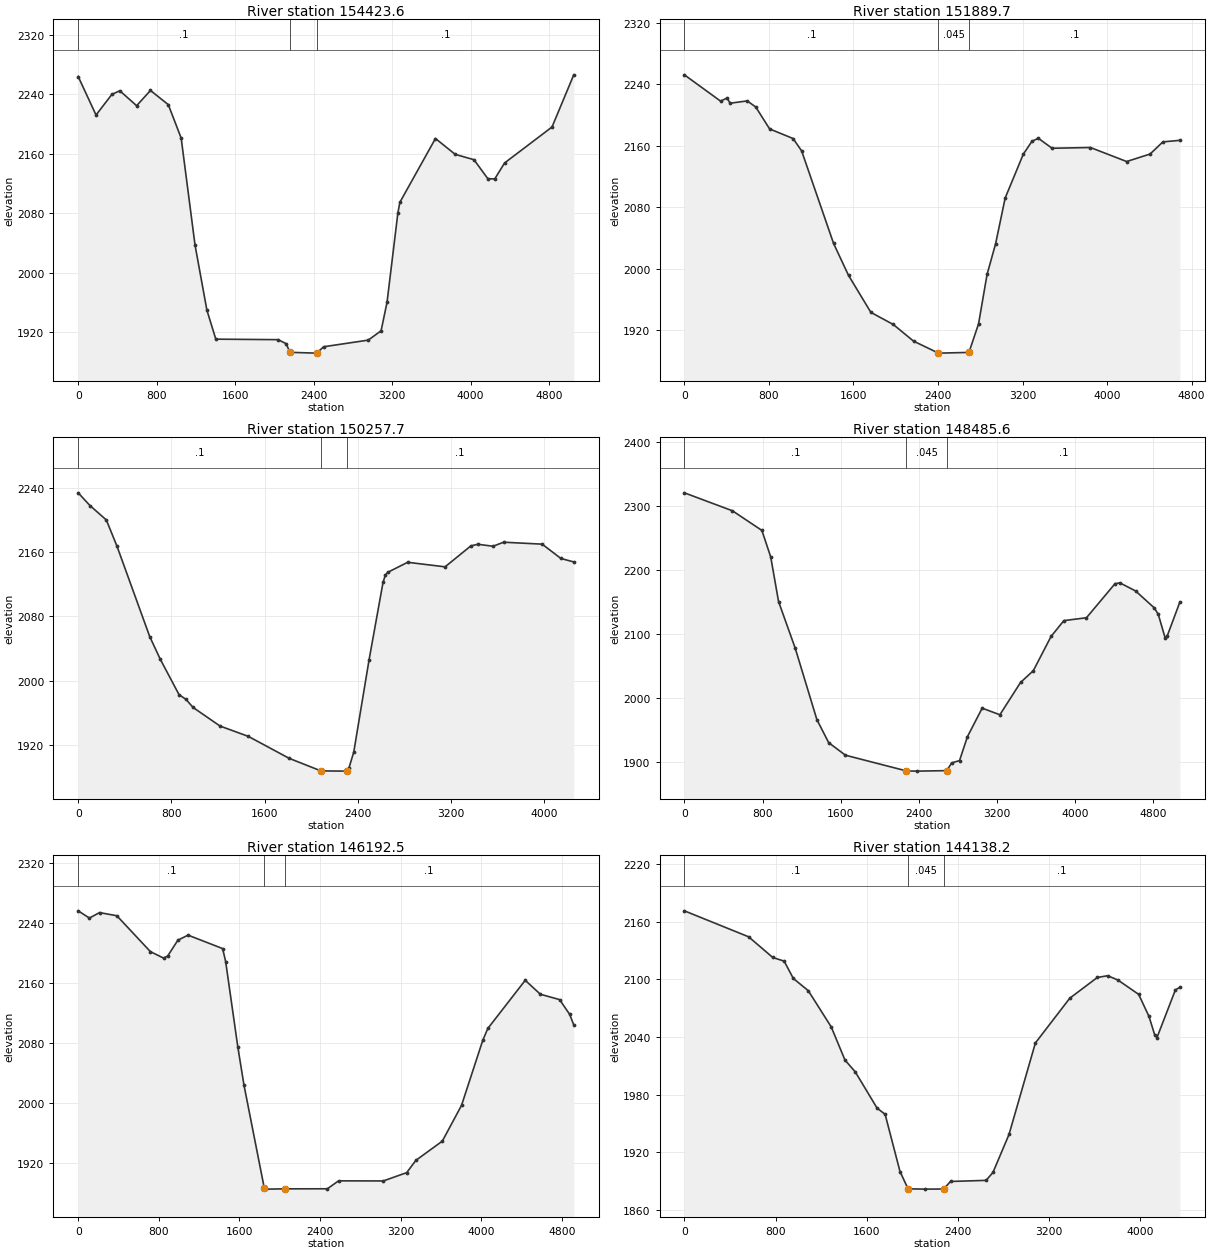
Type RM Length L Ch R = 1 ,154423.6,2516,2533.9,2551.6
XS GIS Cut Line= 4
     2172682.691      371544.381     2172150.359      372518.872
     2171500.718      374609.537     2170614.843       376121.43
#Sta/Elev= 30
       0 2263.99   181.7 2212.18   343.2 2239.88     424 2244.84   595.6 2224.71
   736.9 2245.22   918.6 2226.11  1049.8 2181.08  1191.1 2037.04  1312.2 1949.31
    1403 1910.37  2038.6 1909.69  2119.3 1904.29  2159.6 1892.64    2422 1891.56
    2432 1891.75  2502.7 1900.14  2956.7 1909.06  3087.8 1921.63  3148.4 1959.95
  3259.3 2080.54  3279.5 2094.67  3642.1 2180.54  3843.5 2159.19  4034.8    2152
  4175.8 2126.47  4246.3 2126.06    4347 2147.62  4830.4 2196.02    5052 2266.28
#Mann= 3 , 0 , 0
       0      .1       0  2159.6    .045       0    2432      .1       0
Bank Sta=2159.6,2432
XS Rating Curve= 0 ,0
Exp/Cntr=0.3,0.1

Type RM Length L Ch R = 1 ,151889.7,1622.3,1632,1641.7
XS GIS Cut Line= 3
     2172013.895      371420.794     2169106.841       372934.99
     2168415.175       374165.48
#Sta/Elev= 30
       0 2252.04   342.9 2217.84   403.4 2221.84   433.7 2215.14     595 2218.14
   675.7 2210.16   806.8  2181.7  1028.7 2169.24  1109.4 2153.21    1412 2032.82
  1553.2 1991.35    1765 1943.24  1976.8 1927.52  2168.4  1905.9  2402.9  1890.4
  2410.4 1890.28  2692.8  1891.2  2783.6 1928.22  2864.3 1992.57    2945 2032.41
  3035.7 2091.94  3207.2  2148.9  3287.8  2165.4  3348.3 2169.68  3479.4 2156.58
  3842.4 2157.56  4185.2 2139.33    4407  2149.1    4528 2164.89  4689.3 2166.88
#Mann= 3 , 0 , 0
       0      .1       0  2402.9    .045       0  2692.8      .1       0
Bank Sta=2402.9,2692.8
XS Rating Curve= 0 ,0
Exp/Cntr=0.3,0.1

Type RM Length L Ch R = 1 ,150257.7,1780.8,1772,1763.3
XS GIS Cut Line= 3
     2171843.003      370918.872     2169197.443      371042.414
     2167716.232      371666.632
#Sta/Elev= 30
       0  2233.4   100.7 2217.62   241.7 2199.67   332.3 2167.36   614.3 2054.67
   704.9 2026.52     866  1982.5   926.4 1976.55   986.9 1966.56  1218.5 1943.45
  1460.2 1930.69  1812.6 1903.29  2084.5 1887.74    2296 1887.44  2306.1 1887.56
  2326.2  1891.8  2366.5  1911.1  2497.4 2025.31  2618.2 2122.27  2638.4 2131.35
  2658.5 2134.58  2829.3 2147.05  3150.8  2141.4  3371.8  2167.4    3432 2169.48
  3562.6 2166.98    3653 2172.01  3984.6  2169.6  4145.3  2151.8  4255.8 2147.48
#Mann= 3 , 0 , 0
       0      .1       0  2084.5    .045       0  2306.1      .1       0
Bank Sta=2084.5,2306.1
XS Rating Curve= 0 ,0
Exp/Cntr=0.3,0.1

Type RM Length L Ch R = 1 ,148485.6,2311.4,2293.1,2274.8
XS GIS Cut Line= 3
     2172331.219      368992.386     2171146.368      368833.632
     2167609.935      370425.759
#Sta/Elev= 30
       0 2320.52   492.2 2292.49   793.6 2261.87     884  2220.5   964.4 2150.85
  1135.2 2077.92  1356.6 1966.69  1477.5 1930.69  1648.8 1911.11  2273.3 1886.59
  2384.1 1886.26  2686.3 1887.02  2736.7 1899.03  2817.3 1902.73  2897.9 1939.97
    3049 1984.53  3230.3 1974.21  3441.8 2024.61  3572.8 2043.03  3754.1 2096.39
  3885.1 2121.11  4116.8 2125.61  4408.9 2178.71  4459.3 2180.02  4620.4 2167.33
  4811.8 2140.86  4852.1 2130.85  4922.6 2093.91  4942.8 2096.84  5073.7 2150.34
#Mann= 3 , 0 , 0
       0      .1       0  2273.3    .045       0  2686.3      .1       0
Bank Sta=2273.3,2686.3
XS Rating Curve= 0 ,0
Exp/Cntr=0.3,0.1

Type RM Length L Ch R = 1 ,146192.5,2050.6,2054.4,2058.3
XS GIS Cut Line= 4
     2169916.231      365940.733     2169020.268      367097.318
     2168311.568      369105.301     2167340.187      370005.218
#Sta/Elev= 30
       0 2256.37     111 2246.72   211.9 2254.02   383.4  2249.8   716.4 2201.88
   847.5 2193.23   887.9 2196.05   988.8 2217.13  1089.7 2223.91  1432.8 2205.98
    1463 2188.67  1584.1 2074.23  1644.7  2023.7  1846.5 1885.99  1866.7 1884.76
  2048.4 1885.14  2472.2 1885.22  2583.2 1895.82  3027.3 1895.69  3259.4 1906.78
  3350.2 1923.19  3612.5 1948.83  3803.1 1996.58  4013.7  2083.4  4063.9 2099.28
  4435.1 2163.59  4585.5 2144.98  4776.1 2137.82  4876.4 2118.04  4916.6 2104.06
#Mann= 3 , 0 , 0
       0      .1       0  1846.5    .045       0  2048.4      .1       0
Bank Sta=1846.5,2048.4
XS Rating Curve= 0 ,0
Exp/Cntr=0.3,0.1

Type RM Length L Ch R = 1 ,144138.2,2136.8,2150,2163
XS GIS Cut Line= 3
     2167624.544      365844.415     2166539.564      368533.943
     2166738.222      369970.396
#Sta/Elev= 30
       0 2171.33   563.9  2144.3   775.4 2122.83   876.1 2118.92   956.6  2100.9
  1087.6 2088.23    1289 2050.54  1409.8    2016  1500.4 2003.68  1691.7 1965.98
  1762.2 1959.54  1893.1  1899.9  1963.6 1881.99  2114.7 1881.66  2275.8 1881.78
  2336.2 1889.63  2648.4 1890.78  2708.8    1899  2849.8 1938.55  3081.4 2033.81
  3383.5 2080.41  3625.2 2101.98  3715.8  2103.8  3806.5 2099.24  3987.7 2084.41
  4078.4 2061.46  4128.7 2042.27  4148.8 2039.43    4310 2088.91  4350.2 2091.77
#Mann= 3 , 0 , 0
       0      .1       0  1963.6    .045       0  2275.8      .1       0
Bank Sta=1963.6,2275.8
XS Rating Curve= 0 ,0
Exp/Cntr=0.3,0.1

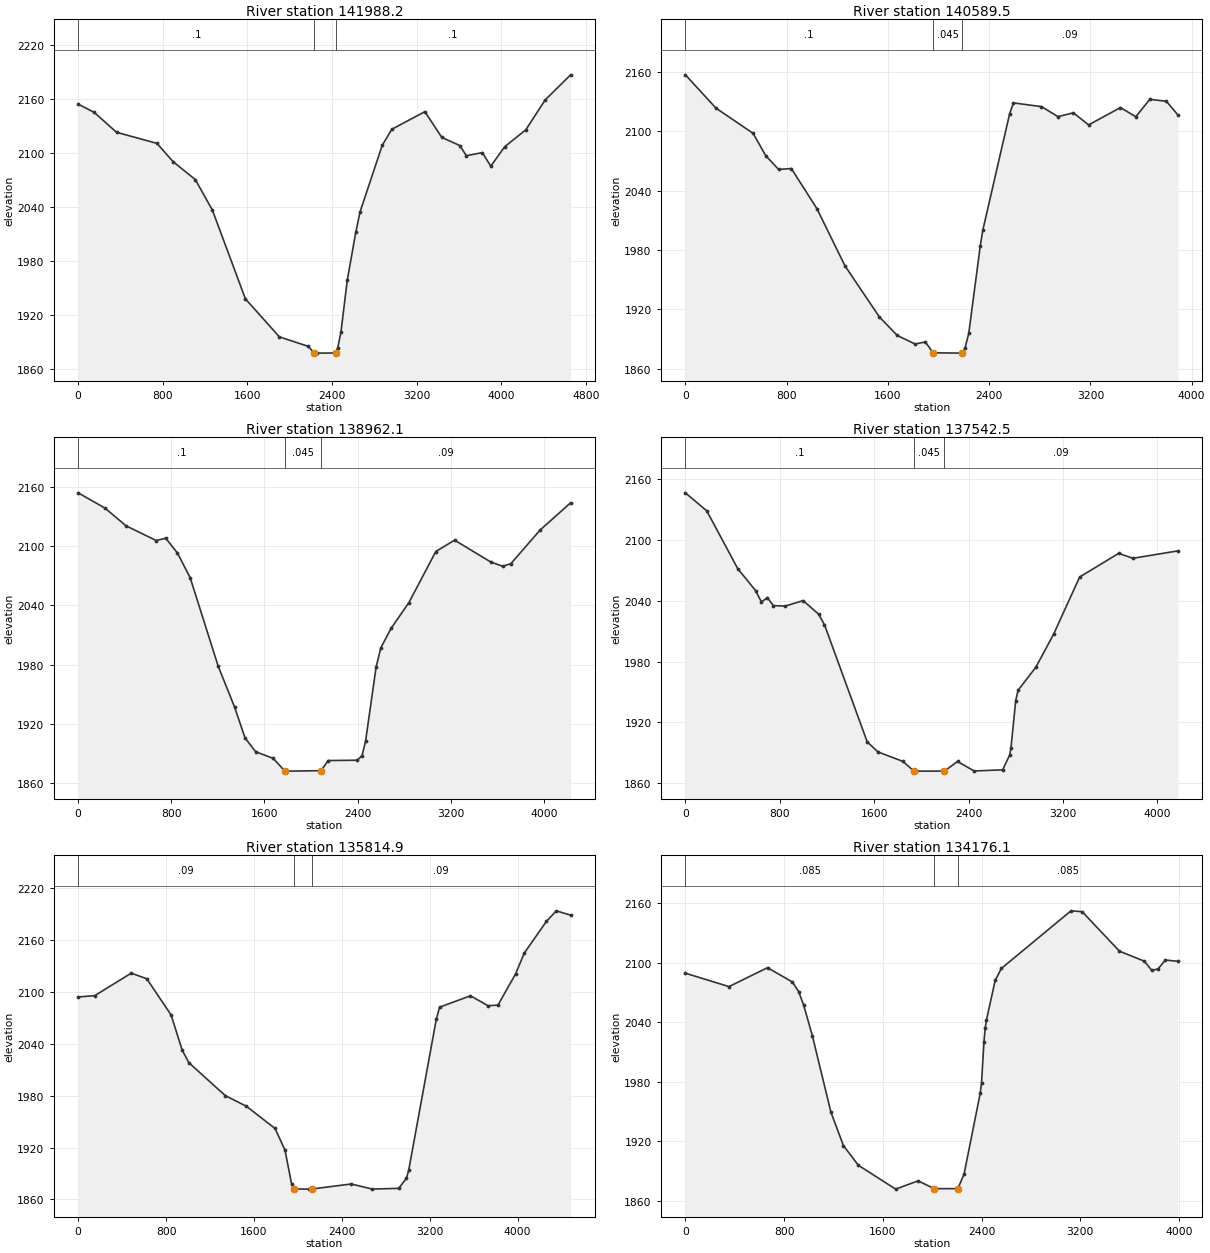
Type RM Length L Ch R = 1 ,141988.2,1394.7,1398.7,1402.5
XS GIS Cut Line= 4
     2166993.816      365395.951     2165854.741      366506.734
     2164720.822      367109.129      2163788.91      368625.632
#Sta/Elev= 30
       0 2153.79     151 2144.72   362.5 2122.56   745.2  2110.2   896.2 2090.06
  1107.7 2069.95  1268.8 2036.13    1581 1937.55    1902 1895.33  2172.8 1884.88
    2233 1877.58  2253.1 1877.26  2433.6 1877.42  2453.7 1883.13  2483.8 1900.27
    2544 1958.39  2624.2 2011.36  2664.4 2034.04    2875 2108.24  2965.5 2125.92
  3277.3 2145.42  3438.2 2116.81  3609.1 2107.75  3669.5 2096.51  3820.3 2099.97
  3900.8 2084.92  4031.5 2106.44  4232.6 2125.42  4413.6 2158.32    4655 2186.36
#Mann= 3 , 0 , 0
       0      .1       0    2233    .045       0  2433.6      .1       0
Bank Sta=2233,2433.6
XS Rating Curve= 0 ,0
Exp/Cntr=0.3,0.1

Type RM Length L Ch R = 1 ,140589.5,1632.9,1627.4,1622
XS GIS Cut Line= 3
     2166751.721      364891.161     2164323.759      365676.319
     2163040.121      366058.355
#Sta/Elev= 30
       0 2156.85   242.1 2123.15   534.6 2097.81   635.4 2075.09   736.3 2061.31
   837.1 2062.19  1038.9 2021.75  1260.8 1963.93  1533.1 1912.23  1674.3 1893.59
  1815.5  1884.9  1896.2 1887.09  1956.7 1876.07  2178.6 1875.74  2188.7 1875.86
  2208.8 1880.61  2239.1 1895.67  2329.9  1984.1    2350 1999.88  2561.8 2117.42
    2592 2128.51  2813.6 2124.72  2944.5 2114.61  3065.3 2118.48  3186.2 2106.29
  3437.9 2123.79  3558.7  2114.5  3669.5 2132.09  3800.4 2130.14    3891 2116.46
#Mann= 3 , 0 , 0
       0      .1       0  1956.7    .045       0  2188.7     .09       0
Bank Sta=1956.7,2188.7
XS Rating Curve= 0 ,0
Exp/Cntr=0.3,0.1

Type RM Length L Ch R = 1 ,138962.1,1430.8,1419.6,1408.5
XS GIS Cut Line= 4
     2166264.498      363659.173      2164992.49      363612.876
     2163693.207      364416.069     2162571.098      365301.944
#Sta/Elev= 30
       0 2154.27   230.5 2138.77   410.9 2120.85   671.5 2105.83   751.7 2108.27
   851.9 2093.39   962.2 2068.17  1202.7 1978.49  1343.2 1937.08  1433.6 1905.68
  1524.1 1891.66  1674.8 1884.99  1775.3 1872.08  1785.4 1871.99  2086.8 1872.43
  2147.1 1882.71  2398.4 1883.06  2438.6 1887.75  2468.7 1902.29  2559.2  1977.3
  2599.4 1997.04  2689.8 2017.08  2840.6 2042.85  3072.2 2094.73  3233.3 2106.27
  3545.4 2084.03  3646.1 2079.79  3716.5 2082.36  3968.2 2116.55    4230 2144.13
#Mann= 3 , 0 , 0
       0      .1       0  1775.3    .045       0  2086.8     .09       0
Bank Sta=1775.3,2086.8
XS Rating Curve= 0 ,0
Exp/Cntr=0.3,0.1

Type RM Length L Ch R = 1 ,137542.5,1729.5,1727.5,1725.6
XS GIS Cut Line= 4
      2164659.95      361321.117     2163740.453      362455.333
     2162963.714      363796.706     2162230.206      364698.309
#Sta/Elev= 30
       0 2146.31   181.2 2128.52   443.1 2071.66   594.1 2050.01   644.5 2038.68
   694.8 2042.98   745.2 2035.14   845.9 2034.68   996.9 2040.08  1127.8 2026.81
  1178.2 2016.35  1540.6 1900.83  1631.2 1890.93  1842.6  1881.6  1933.2 1872.33
  1953.3 1871.99  2194.9 1872.04  2305.6 1881.49  2446.5 1872.13  2688.1 1873.28
  2748.4 1888.06  2758.5 1894.79  2798.8 1941.56  2818.9 1951.72  2969.9 1974.49
  3120.4 2007.13  3340.8 2063.36  3671.4 2086.64  3791.7 2081.78  4172.4 2089.09
#Mann= 3 , 0 , 0
       0      .1       0  1933.2    .045       0  2194.9     .09       0
Bank Sta=1933.2,2194.9
XS Rating Curve= 0 ,0
Exp/Cntr=0.3,0.1

Type RM Length L Ch R = 1 ,135814.9,1643.4,1638.8,1634.1
XS GIS Cut Line= 4
      2163254.06      360709.861     2162077.392      361825.404
     2161374.447      363338.264     2161374.447      364530.214
#Sta/Elev= 30
       0 2094.12   151.1 2095.68   483.4 2121.68   624.4 2115.17     846 2073.31
   946.7  2032.6  1007.1 2018.18  1339.4 1980.02  1530.8 1967.81  1792.2 1942.06
  1882.7 1916.89    1943  1877.6  1963.1 1872.19  2103.8 1871.96  2123.9 1872.08
  2485.7  1877.9  2676.6 1872.02  2917.8 1872.87  2988.1 1884.66  3008.2 1893.79
  3259.5  2068.5  3289.6 2082.36  3570.1 2095.48  3730.3 2084.05  3820.5  2084.7
  3980.7 2120.73  4060.9 2145.04  4261.2 2181.44  4351.4 2193.73  4481.6 2188.74
#Mann= 3 , 0 , 0
       0     .09       0  1963.1    .045       0  2123.9     .09       0
Bank Sta=1963.1,2123.9
XS Rating Curve= 0 ,0
Exp/Cntr=0.3,0.1

Type RM Length L Ch R = 1 ,134176.1,1869.3,1867.3,1865.3
XS GIS Cut Line= 3
     2160865.551      360176.095     2160243.622      362711.726
     2159937.994       364056.49
#Sta/Elev= 30
       0 2089.58   352.8 2076.05   665.3 2095.13   866.9 2080.72   917.3 2071.05
   957.6 2057.64  1028.2 2026.67  1179.4 1949.17  1280.2 1915.65  1401.2 1895.78
  1703.6 1871.69    1885 1880.04    2016 1872.16  2207.6 1872.21    2258 1886.99
    2389 1968.63  2399.1 1978.69  2419.3  2020.4  2429.3 2034.76  2439.4 2042.44
    2510 2082.34  2560.4 2094.41  3124.2 2152.51  3214.8 2151.65  3516.7 2111.82
  3718.1 2101.71  3778.5 2092.46  3828.8 2093.79  3889.2 2102.88  3989.8 2101.54
#Mann= 3 , 0 , 0
       0    .085       0    2016    .045       0  2207.6    .085       0
Bank Sta=2016,2207.6
XS Rating Curve= 0 ,0
Exp/Cntr=0.3,0.1