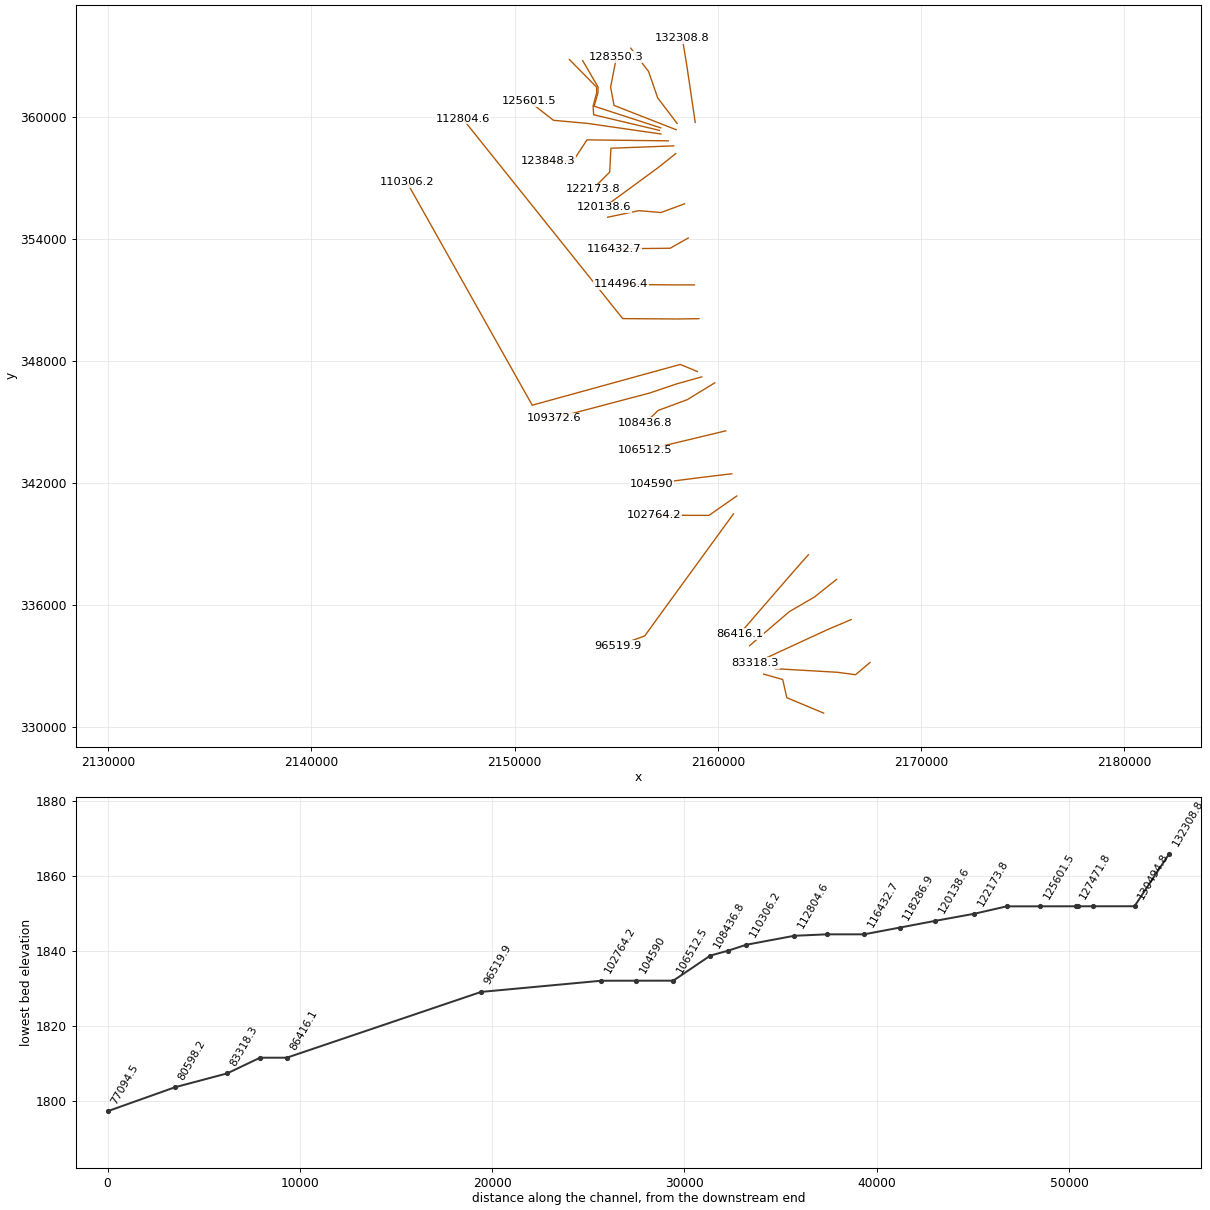
HEC-RAS study GrnbrRv.prj: GrnbrRv

--- GrnbrRv.g01 (geometry) --- (continued)

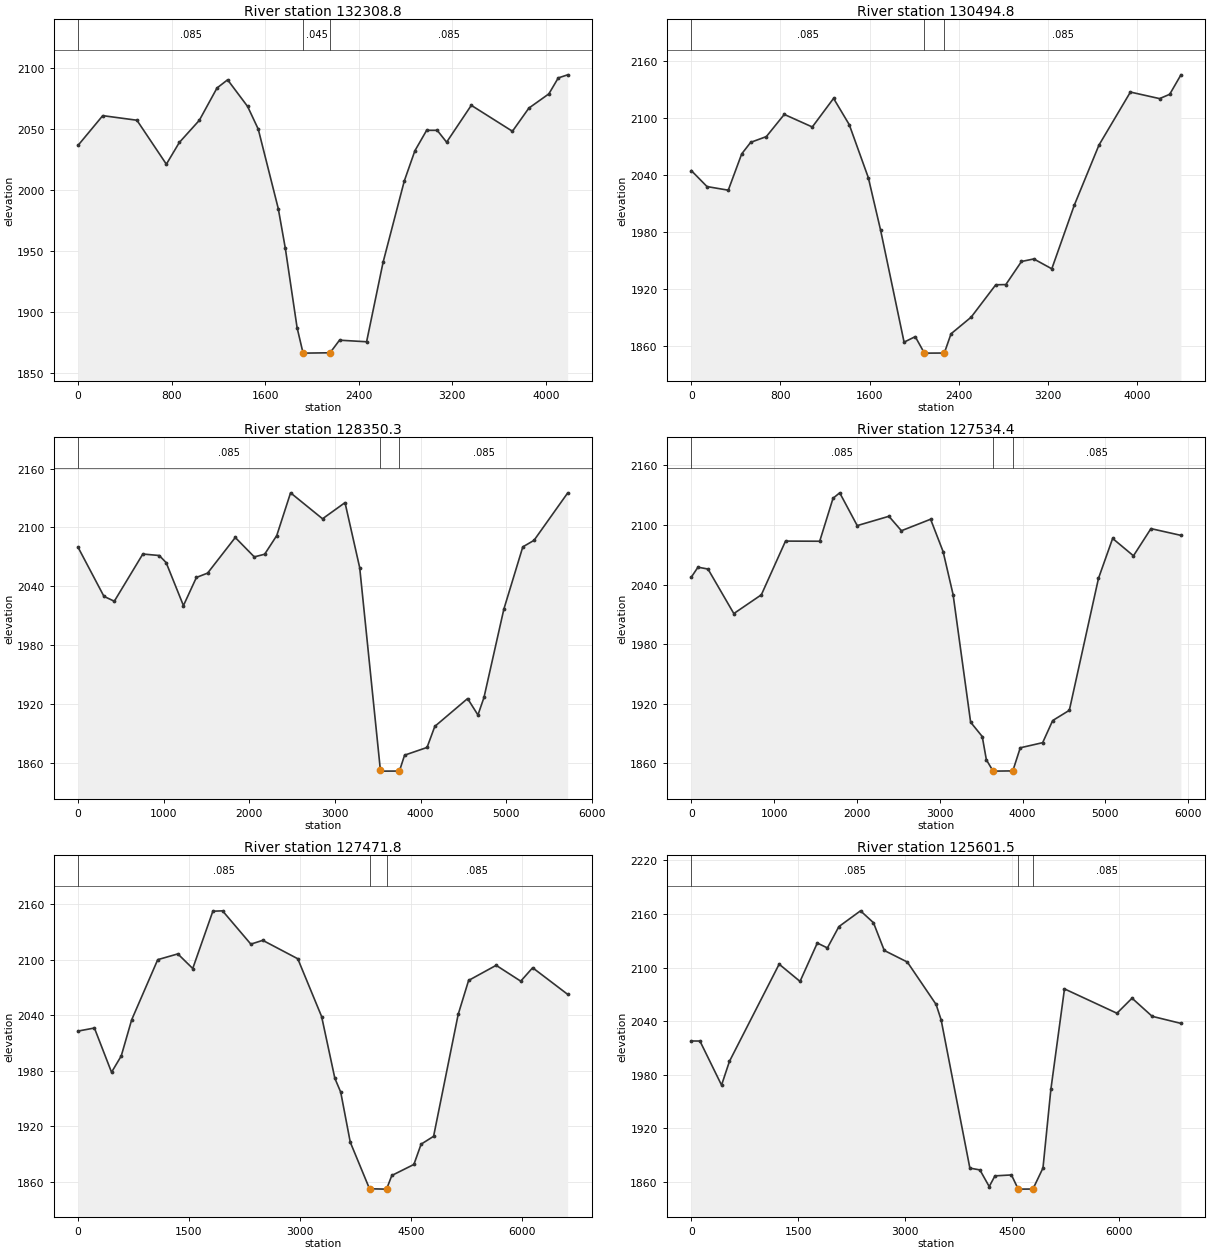
Type RM Length L Ch R = 1 ,132308.8,1809.8,1814,1818.2
XS GIS Cut Line= 3
     2158891.076      359734.494     2158470.979      362574.193
     2158257.039      363873.113
#Sta/Elev= 30
       0 2036.49   211.5 2060.91   503.6 2057.14   755.4 2021.07   866.2  2038.9
  1037.4 2057.09  1188.5  2083.6  1279.2 2090.31  1450.4 2068.42  1541.1 2049.85
  1712.3 1984.68  1772.7 1952.08  1873.4 1886.94  1923.8 1866.33  1933.9 1866.09
  2155.5 1866.38    2236 1876.71  2467.7 1875.41  2608.7 1940.65    2790 2007.31
  2880.6 2032.08  2981.1 2048.87  3071.6 2048.85    3152 2039.13    3363 2069.38
  3714.7 2048.09  3855.4  2067.1  4026.2 2078.76  4106.6 2091.85    4187 2094.39
#Mann= 3 , 0 , 0
       0    .085       0  1923.8    .045       0  2155.5    .085       0
Bank Sta=1923.8,2155.5
XS Rating Curve= 0 ,0
Exp/Cntr=0.3,0.1

Type RM Length L Ch R = 1 ,130494.8,2147.8,2144.5,2141.2
XS GIS Cut Line= 4
     2157997.255      359686.006     2157043.239       360943.44
     2156594.396      362242.723     2155720.333      363388.455
#Sta/Elev= 30
       0 2044.23   140.8 2027.38   331.8 2023.55   452.4  2061.8   532.8 2073.92
   673.6    2080   834.4 2103.35  1085.8 2090.12  1276.8 2120.24  1417.5 2092.58
  1588.4 2036.82  1698.8 1981.49  1909.5 1863.55  2009.8 1869.35  2090.1 1852.35
  2110.2 1851.99  2270.7 1852.09  2330.9 1872.34  2511.5 1889.87  2732.3 1923.96
  2822.6 1924.17  2963.1 1948.48  3073.9 1951.16  3235.2 1940.78  3436.7 2007.66
  3658.4 2071.05  3940.6 2126.88  4202.6 2119.99  4293.3 2124.53  4394.1 2145.03
#Mann= 3 , 0 , 0
       0    .085       0  2090.1    .045       0  2270.7    .085       0
Bank Sta=2090.1,2270.7
XS Rating Curve= 0 ,0
Exp/Cntr=0.3,0.1

Type RM Length L Ch R = 1 ,128350.3,826.7,815.9,805.1
XS GIS Cut Line= 4
     2157957.071      359373.869     2154895.129      360572.328
     2154727.033      361473.931      2155017.38      362956.228
#Sta/Elev= 30
       0 2079.89   302.6 2029.88   423.6  2024.9   756.5 2072.96   948.1 2071.45
  1028.8 2064.22  1230.5 2020.45  1381.8 2049.11  1512.9 2053.55  1835.7 2089.78
  2057.6 2070.04  2178.6 2072.76  2319.8 2091.75  2481.2 2135.25  2854.4 2108.84
  3116.7 2125.27  3288.1 2059.08    3530 1852.66  3540.1 1851.98  3751.7 1852.05
  3812.2 1868.23  4074.2 1876.08    4165 1897.52  4547.6 1925.84  4668.5 1909.12
    4739 1926.98  4970.6 2016.75  5192.1 2080.23    5323 2086.88  5715.7 2135.08
#Mann= 3 , 0 , 0
       0    .085       0    3530    .045       0  3751.7    .085       0
Bank Sta=3530,3751.7
XS Rating Curve= 0 ,0
Exp/Cntr=0.3,0.1

Type RM Length L Ch R = 1 ,127534.4,62.4,62.7,62.9
XS GIS Cut Line= 5
      2157194.57      359466.206     2153919.983      360531.219
     2154106.055      361204.564     2154109.045      361476.622
     2153354.731      362771.391
#Sta/Elev= 30
       0 2047.45    80.6 2057.49   201.4 2055.62   513.5 2010.76   845.8 2029.66
  1137.7 2083.78  1550.6 2083.65  1711.6 2126.95  1792.2 2132.42  2003.6 2099.39
  2386.2 2108.78  2537.3 2094.22  2889.7  2105.8  3040.7  2073.2  3161.5 2029.78
    3373  1901.3  3513.3 1886.85  3563.2 1863.39    3643 1852.21    3653 1851.98
  3882.5 1852.22  3972.4 1875.49  4242.8 1880.66  4363.7 1902.94  4564.9 1913.27
  4916.9 2046.21  5087.9 2086.45  5339.3 2068.95  5550.5 2096.35  5912.6 2089.55
#Mann= 3 , 0 , 0
       0    .085       0    3643    .045       0  3882.5    .085       0
Bank Sta=3643,3882.5
XS Rating Curve= 0 ,0
Exp/Cntr=0.3,0.1

Type RM Length L Ch R = 1 ,127471.8,1830.2,1870.2,1909.8
XS GIS Cut Line= 6
     2157125.399      359345.155     2153892.453      360110.773
     2153864.924      360536.225     2154043.272      361206.059
     2154040.283      361469.148     2152697.751      362831.116
#Sta/Elev= 30
       0 2022.85   221.5 2026.17     453 1978.34   583.9 1995.91   724.9 2035.02
  1077.2 2100.06  1349.1 2106.29  1550.4  2090.5  1822.3 2152.44  1953.2 2152.86
  2335.7 2116.85  2496.8 2120.96    2970 2101.04  3292.2 2038.59  3471.1 1971.79
  3550.4 1956.81  3679.3 1902.76  3939.6 1852.36  4160.6 1851.98  4170.6 1852.17
    4241 1866.74  4539.3 1878.66  4636.8 1900.58  4805.6 1909.08  5137.8 2040.87
  5278.7 2077.61  5651.1 2093.94  5983.3 2076.81  6144.3 2091.32  6617.4 2062.57
#Mann= 3 , 0 , 0
       0    .085       0  3939.6    .045       0  4170.6    .085       0
Bank Sta=3939.6,4170.6
XS Rating Curve= 0 ,0
Exp/Cntr=0.3,0.1

Type RM Length L Ch R = 1 ,125601.5,1728.8,1753.2,1777.6
XS GIS Cut Line= 4
     2157202.622      359166.438     2153596.209      359686.006
     2151915.253       359838.82     2150706.902      360780.542
#Sta/Elev= 30
       0 2017.79   121.1 2017.74   423.9 1968.38   534.9 1995.04  1231.4 2103.79
  1524.1 2084.48  1766.3 2127.45  1907.6 2121.94  2069.1 2145.84  2371.9 2163.48
  2553.6 2150.18    2705 2119.12    3028 2106.17  3431.7 2058.67  3502.3 2041.36
  3904.9  1875.5  4045.5 1873.47  4176.1 1854.84  4256.5 1866.81  4487.6 1867.86
  4580.6 1852.34  4595.6 1851.97    4789 1852.09  4929.7 1875.62  5040.2 1963.53
  5231.1  2076.1  5966.5 2048.85  6178.2  2065.7  6460.4 2045.39  6863.5 2037.48
#Mann= 3 , 0 , 0
       0    .085       0  4580.6    .045       0    4789    .085       0
Bank Sta=4580.6,4789
XS Rating Curve= 0 ,0
Exp/Cntr=0.3,0.1

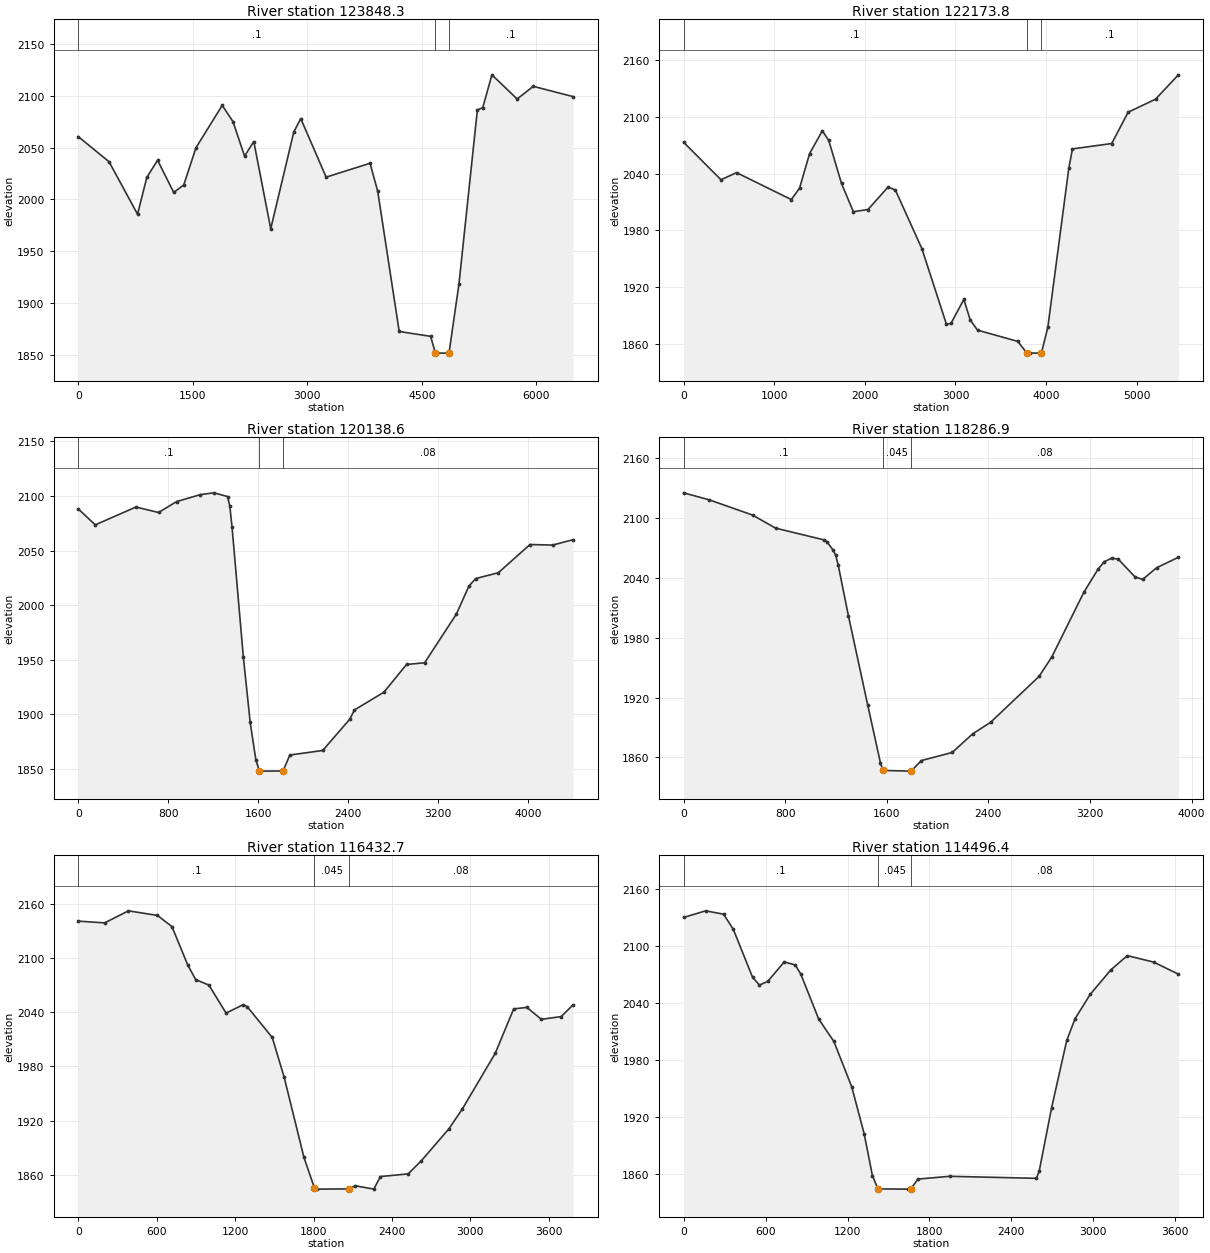
Type RM Length L Ch R = 1 ,123848.3,1662.6,1674.5,1686.4
XS GIS Cut Line= 4
     2157569.278        358827.9     2153565.646      358876.092
     2152893.264      357852.237     2151640.188      357821.674
#Sta/Elev= 30
       0 2060.52   403.4  2036.3   776.6 1985.75   897.6 2021.14  1038.8 2037.78
  1250.6 2006.72  1381.7 2013.94  1543.1 2049.97    1886 2090.57  2027.2 2074.92
  2178.5 2041.71  2299.5 2055.76  2521.4 1971.73  2823.9 2065.02  2914.7 2077.89
  3247.5 2021.46  3822.4 2034.83  3923.2 2007.83  4204.7  1872.8  4616.4 1868.13
  4676.6 1852.54  4696.7 1851.96  4857.3 1852.01  4987.9 1918.71  5228.8 2086.26
    5299 2088.33  5419.3 2120.02  5750.2 2096.73  5960.8 2108.94  6482.3 2099.04
#Mann= 3 , 0 , 0
       0      .1       0  4676.6    .045       0  4857.3      .1       0
Bank Sta=4676.6,4857.3
XS Rating Curve= 0 ,0
Exp/Cntr=0.3,0.1

Type RM Length L Ch R = 1 ,122173.8,2055.2,2035.2,2015.2
XS GIS Cut Line= 4
     2157832.524      358580.891     2154742.315      358463.493
     2154681.189      357286.825     2153840.711      356446.347
#Sta/Elev= 30
       0 2073.23     413 2033.52   584.2 2041.08  1188.6 2012.56  1279.3 2024.56
  1390.1 2061.15  1531.1 2085.39  1601.6 2075.16  1742.6 2029.58  1873.6 1999.69
  2034.8 2002.03  2256.4 2025.82    2337 2022.67  2629.1 1960.65    2901 1880.38
  2951.4 1881.61  3092.4 1906.84  3162.9  1885.1  3243.5 1874.32  3686.6 1862.44
  3787.3 1850.16    3825 1849.99  3948.4 1850.13  4018.9  1877.2  4250.6  2045.7
  4290.8 2066.17    4724 2071.91  4905.3 2105.05  5207.5 2118.81  5459.3 2144.62
#Mann= 3 , 0 , 0
       0      .1       0  3787.3    .045       0  3948.4      .1       0
Bank Sta=3787.3,3948.4
XS Rating Curve= 0 ,0
Exp/Cntr=0.3,0.1

Type RM Length L Ch R = 1 ,120138.6,1867.8,1851.7,1835.5
XS GIS Cut Line= 3
     2157936.129      358203.709     2157095.652      357531.327
     2154411.598      355565.276
#Sta/Elev= 30
       0  2088.2   150.9 2073.55     513 2089.91   714.2 2084.89   875.2 2094.89
  1086.4 2101.27  1207.4  2102.9  1328.4 2099.52  1348.6  2090.8  1368.7 2071.34
  1469.5 1952.15    1530  1892.7  1580.4 1858.46  1610.7 1848.46  1620.8 1848.09
  1822.4 1848.21  1882.9 1862.84  2175.3 1866.99  2417.2 1895.77  2457.6  1904.1
  2719.7 1920.32  2921.4 1945.73  3082.7 1947.32    3365 1991.87  3475.9 2017.38
  3536.4 2024.41    3738 2029.71  4020.3 2055.57    4222 2055.05  4403.4    2060
#Mann= 3 , 0 , 0
       0      .1       0  1610.7    .045       0  1822.4     .08       0
Bank Sta=1610.7,1822.4
XS Rating Curve= 0 ,0
Exp/Cntr=0.3,0.1

Type RM Length L Ch R = 1 ,118286.9,1853.4,1854.2,1856.5
XS GIS Cut Line= 4
     2158364.009      355728.121     2157202.622      355300.241
     2156117.642       355391.93     2154582.327      355069.107
#Sta/Elev= 30
       0 2125.43   201.2 2118.44   543.4  2103.1   724.5    2090  1106.9  2078.2
    1127 2076.56  1177.3 2067.97  1197.4 2062.86  1217.6  2052.8  1298.2 2001.83
  1449.4 1912.74  1550.2 1854.42  1570.4    1847  1782.1 1846.28  1792.2 1846.44
  1872.9 1856.91  2114.8 1864.99  2276.1 1883.69  2417.1 1895.26  2799.2 1941.32
  2899.8    1961  3151.2 2025.62  3261.8  2048.6  3312.1 2056.34  3372.5 2060.01
  3422.8  2058.8  3553.5 2041.21  3613.8 2038.53  3724.5 2050.29  3895.4 2060.77
#Mann= 3 , 0 , 0
       0      .1       0  1570.4    .045       0  1792.2     .08       0
Bank Sta=1570.4,1792.2
XS Rating Curve= 0 ,0
Exp/Cntr=0.3,0.1

Type RM Length L Ch R = 1 ,116432.7,1935.3,1936.3,1935.8
XS GIS Cut Line= 3
     2158547.386      354047.166     2157661.064      353542.879
     2154895.129      353512.316
#Sta/Elev= 30
       0  2140.6   201.9 2138.65   383.7 2151.98   605.8 2146.89   716.8 2134.53
     838 2092.01   898.6 2075.99   999.6 2069.89  1130.8 2038.98    1262  2048.3
  1292.3 2046.12  1484.1 2012.06    1575 1968.38  1726.4 1879.64  1807.2 1845.73
  1827.4 1844.48  2069.6 1844.74  2120.1 1848.18  2261.5 1844.51  2311.9 1858.38
  2523.9 1861.31  2624.9 1875.79  2836.9 1911.31  2937.8 1932.84  3190.2 1994.51
  3331.6 2043.63  3432.5 2045.29  3543.6 2032.09    3695 2035.14  3785.8  2048.1
#Mann= 3 , 0 , 0
       0      .1       0  1807.2    .045       0  2069.6     .08       0
Bank Sta=1807.2,2069.6
XS Rating Curve= 0 ,0
Exp/Cntr=0.3,0.1

Type RM Length L Ch R = 1 ,114496.4,1691.7,1691.8,1691.8
XS GIS Cut Line= 3
     2158853.014      351739.673     2157752.752      351739.673
     2155230.995      351760.889
#Sta/Elev= 30
       0 2129.92   161.5 2136.92   292.7 2133.38   363.4 2117.68   504.7 2067.26
   555.2 2058.89   615.7 2062.75   736.9  2083.2   817.6 2080.06     858 2070.48
   989.2 2023.17  1100.3 1999.66  1231.4 1951.85  1322.2 1902.51  1382.7 1858.54
  1423.1 1844.68    1645 1844.48  1665.2 1845.02  1715.6 1855.04  1947.6 1857.95
  2583.1 1855.83  2603.3 1863.44  2694.1 1929.92    2805 2000.68  2865.6 2023.51
  2976.5 2049.04  3127.8 2074.91  3248.9 2089.82  3440.5 2083.08  3622.1  2070.4
#Mann= 3 , 0 , 0
       0      .1       0  1423.1    .045       0  1665.2     .08       0
Bank Sta=1423.1,1665.2
XS Rating Curve= 0 ,0
Exp/Cntr=0.3,0.1

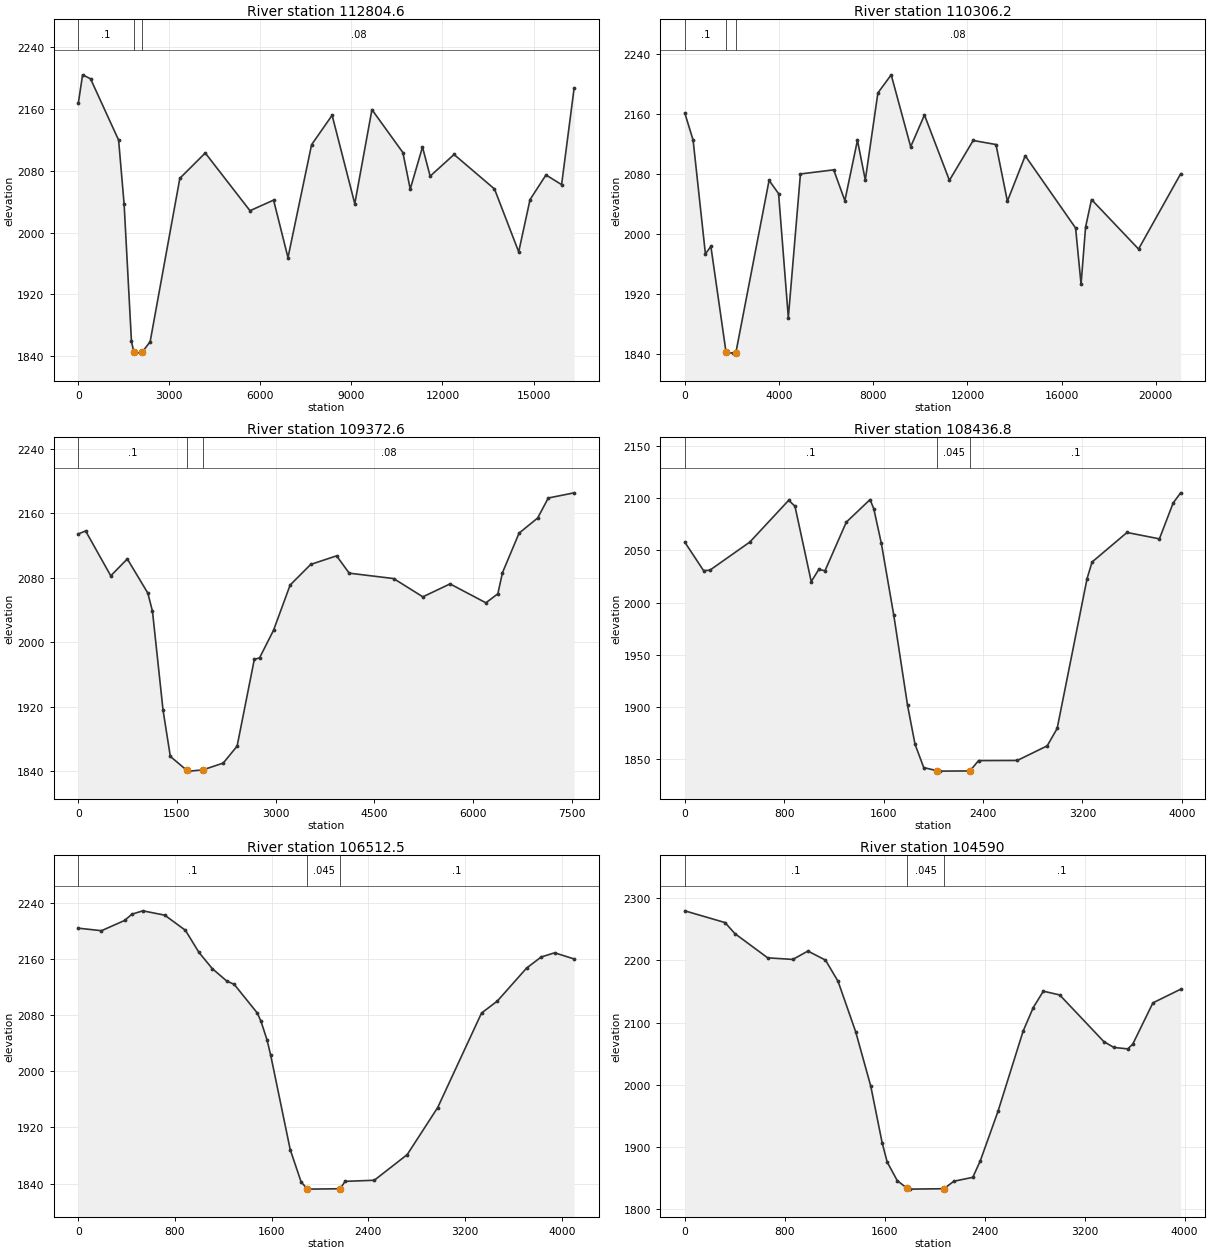
Type RM Length L Ch R = 1 ,112804.6,2491.8,2498.4,2505
XS GIS Cut Line= 4
     2159070.829      350076.994     2157985.849      350061.712
     2155322.429      350080.139     2147453.848      359909.032
#Sta/Elev= 30
       0 2167.64   140.7 2204.21   401.9 2199.09  1327.2 2119.77  1508.8 2036.89
    1751 1859.24 1830.75 1845.11    2094 1844.09  2114.2 1845.89  2366.4 1858.87
    3345  2070.3  4182.7 2103.08  5656.8 2028.38  6434.3 2042.11  6908.8 1967.73
  7686.3 2113.77  8362.8 2151.89  9109.9 2037.44  9675.3 2159.17 10695.1 2103.64
 10937.4 2056.34 11341.3  2110.8 11593.7 2073.07 12381.2 2101.13   13714 2056.49
 14511.6 1975.12 14885.2 2042.74 15410.2 2074.64 15925.2 2062.14 16339.1 2187.37
#Mann= 3 , 0 , 0
       0      .1       0 1830.75    .045       0  2114.2     .08       0
Bank Sta=1830.75,2114.2
XS Rating Curve= 0 ,0
Exp/Cntr=0.3,0.1

Type RM Length L Ch R = 1 ,110306.2,932.8,933.6,934.5
XS GIS Cut Line= 4
     2159000.299      347474.377       2158154.4      347824.754
     2150869.839      345818.065     2144705.042      356786.602
#Sta/Elev= 30
       0 2160.97   352.2 2125.04   875.4 1973.56  1107.3 1983.69  1752.9 1842.53
  2065.6 1841.69  2166.5 1842.01  3578.8 2071.43  3982.3 2053.81    4396 1888.94
  4910.4 2079.96  6322.8  2085.4  6796.9 2044.45  7331.6 2124.81  7664.4 2071.83
  8199.1 2187.68  8764.1 2211.78  9591.5 2116.14 10176.7 2158.35 11236.2 2071.45
 12245.2 2124.48 13213.8  2119.1 13698.1 2043.72 14454.9 2104.12   16594 2008.08
   16826 1933.34 17017.8 2009.25   17270 2045.94 19267.8 1980.11 21053.8 2080.06
#Mann= 3 , 0 , 0
       0      .1       0  1752.9    .045       0  2166.5     .08       0
Bank Sta=1752.9,2166.5
XS Rating Curve= 0 ,0
Exp/Cntr=0.3,0.1

Type RM Length L Ch R = 1 ,109372.6,935.1,935.8,936.4
XS GIS Cut Line= 4
     2159208.217      347211.744     2157977.172      346867.989
     2156653.863      346419.321     2151951.768      345177.623
#Sta/Elev= 30
       0 2134.59   110.7  2138.3   493.1 2082.59   744.7 2103.57  1056.7 2061.13
  1127.2 2038.56  1288.2 1915.69  1398.8 1858.38  1650.1 1841.08  1687.7 1840.12
  1891.3 1841.61    2203 1850.12  2414.1 1871.15  2675.4 1978.77  2756.2 1980.86
    2968 2015.01  3220.3 2071.16  3533.1 2096.74  3926.6 2107.38  4118.3  2085.9
  4794.3 2079.17  5238.2 2056.51  5651.9 2072.55  6196.8 2049.11  6378.4 2060.26
    6449 2086.59  6701.3  2135.6  6983.8 2154.36  7145.2 2179.19  7538.7 2185.62
#Mann= 3 , 0 , 0
       0      .1       0  1650.1    .045       0  1891.3     .08       0
Bank Sta=1650.1,1891.3
XS Rating Curve= 0 ,0
Exp/Cntr=0.3,0.1

Type RM Length L Ch R = 1 ,108436.8,1927,1924.3,1921.5
XS GIS Cut Line= 4
     2159852.925      346920.253     2158495.607      346088.563
     2157064.538      345560.762      2156439.67      344950.812
#Sta/Elev= 30
       0  2057.8   151.1 2030.56   201.5 2030.96   523.9 2057.94   836.2 2097.86
   886.6 2092.16  1017.6 2020.07    1078 2031.64  1128.4 2030.46  1299.7 2076.93
  1491.1 2098.52  1521.3 2089.59  1581.8 2056.64  1682.2 1987.67  1792.6 1901.82
  1852.8 1864.56    1923 1842.17  2033.4 1839.09  2053.5 1838.79  2294.3 1838.98
  2364.5 1848.88  2675.6 1848.99  2916.5 1862.97  2996.7 1879.59  3237.6 2022.99
  3277.8 2038.79  3558.8 2067.04  3819.7 2060.96  3930.2 2095.22  3990.4 2104.97
#Mann= 3 , 0 , 0
       0      .1       0  2033.4    .045       0  2294.3      .1       0
Bank Sta=2033.4,2294.3
XS Rating Curve= 0 ,0
Exp/Cntr=0.3,0.1

Type RM Length L Ch R = 1 ,106512.5,1925,1922.6,1920.1
XS GIS Cut Line= 3
     2160393.909      344557.923     2158925.309      344202.662
     2156404.507      343602.488
#Sta/Elev= 30
       0 2204.32   191.4 2200.71   382.8 2215.33   443.2 2224.28   533.9 2229.07
   715.2 2222.87   886.4 2201.24   997.2 2169.94    1108  2146.7  1228.9 2128.76
  1289.4 2124.27  1480.7  2083.3    1511 2071.53  1561.4  2044.9  1591.6 2023.01
    1753 1888.47  1843.7 1842.15  1894.1 1832.52  1904.2 1832.09  2166.3 1832.63
  2206.7 1843.16  2448.6 1844.75  2720.9 1881.31    2973 1948.41  3335.9 2083.28
    3467 2100.42    3709 2147.49    3830 2163.26  3940.9 2169.19  4102.2 2160.39
#Mann= 3 , 0 , 0
       0      .1       0  1894.1    .045       0  2166.3      .1       0
Bank Sta=1894.1,2166.3
XS Rating Curve= 0 ,0
Exp/Cntr=0.3,0.1

Type RM Length L Ch R = 1 ,104590  ,1828.6,1825.8,1822.9
XS GIS Cut Line= 3
     2160691.489      342443.871     2159383.481      342288.684
     2156753.646        341952.6
#Sta/Elev= 30
       0 2279.89   321.8 2261.01   402.2 2243.04   663.6 2204.25   864.7 2201.68
   985.4 2215.17  1126.1 2200.58  1226.7 2166.38  1367.6 2085.37  1488.6 1997.68
  1579.3 1906.89  1619.6 1875.75  1700.2 1845.82  1780.9 1833.21  1801.1 1832.08
  2073.2 1832.74  2153.9  1844.8  2305.1 1851.08  2365.6 1877.94  2506.7 1957.25
  2708.3 2086.61    2789 2124.24  2869.6  2150.6  3000.7 2144.52  3353.5 2069.52
  3434.1 2060.08    3545 2057.73  3585.3 2065.41  3746.6  2131.8  3968.4 2153.73
#Mann= 3 , 0 , 0
       0      .1       0  1780.9    .045       0  2073.2      .1       0
Bank Sta=1780.9,2073.2
XS Rating Curve= 0 ,0
Exp/Cntr=0.3,0.1

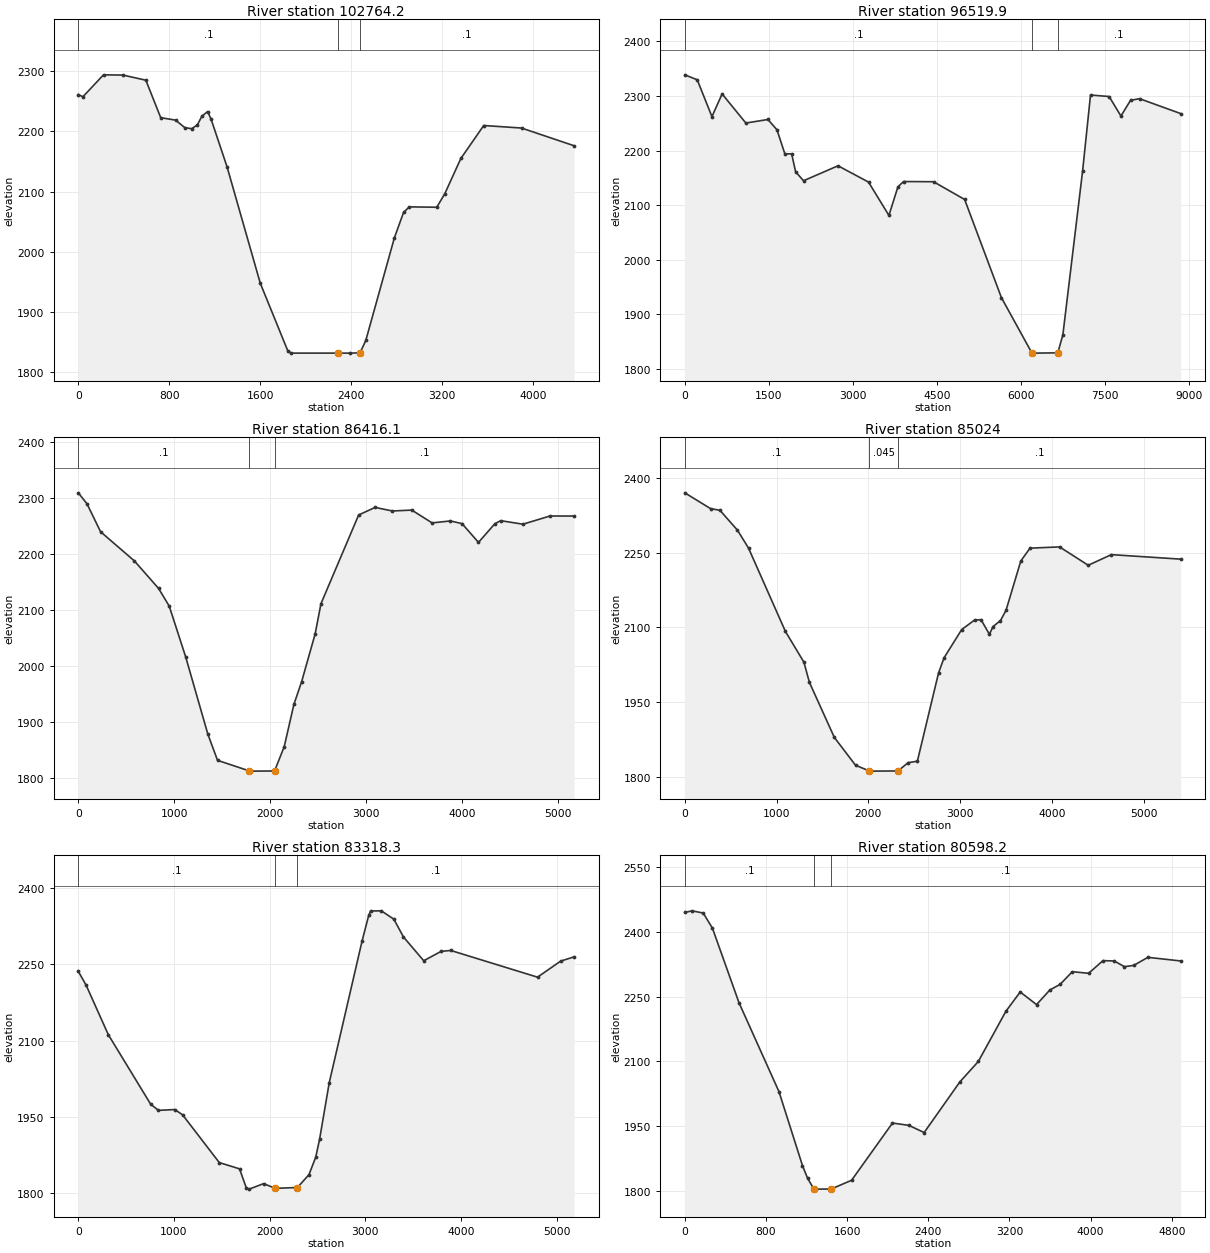
Type RM Length L Ch R = 1 ,102764.2,6223.6,6244.3,6265
XS GIS Cut Line= 4
     2160937.511      341352.451     2159568.228      340396.876
     2158600.154      340396.876     2156879.544       340422.14
#Sta/Elev= 30
       0 2260.79    40.2 2257.02   221.3 2293.41   392.3 2292.99   593.5 2284.49
   724.2  2222.4     855 2218.31   935.5 2205.93   995.8 2204.12  1046.1 2210.31
  1086.3 2224.91  1136.6 2232.55  1166.8 2220.03  1307.6 2140.73  1599.3 1947.97
  1841.2 1835.93  1871.4 1832.09  2284.9 1832.09  2385.7 1832.07  2476.5 1832.52
  2526.9 1853.02  2778.7 2023.48  2859.2  2065.4  2909.5 2074.52    3151 2073.91
  3221.5 2096.32  3362.4 2154.71  3563.6 2209.39  3895.7 2205.22  4358.6  2175.8
#Mann= 3 , 0 , 0
       0      .1       0  2284.9    .045       0  2476.5      .1       0
Bank Sta=2284.9,2476.5
XS Rating Curve= 0 ,0
Exp/Cntr=0.3,0.1

Type RM Length L Ch R = 1 ,96519.9 ,10105.6,10103.8,10101.9
XS GIS Cut Line= 4
     2160772.373      340469.451     2157351.265      335770.813
     2156408.439       334465.85     2155066.637        333979.1
#Sta/Elev= 30
       0 2338.59     222 2329.49   484.4 2262.05     666  2303.6  1089.8  2250.3
  1483.3 2256.81  1644.8 2238.05    1786 2193.84  1907.1 2194.01  1977.8 2161.08
    2119 2144.66  2734.5 2172.06  3279.4 2142.21  3642.7 2081.23  3804.1 2133.55
    3905 2143.24  4439.8 2142.87  4994.8 2110.36  5650.7 1930.76  6194.5  1829.4
  6204.6 1829.08  6657.4 1829.58  6747.9 1862.75  7100.1 2162.57    7241 2301.54
  7572.9  2298.9    7784 2263.18  7954.8 2291.82  8115.7 2294.94  8849.4 2267.68
#Mann= 3 , 0 , 0
       0      .1       0  6194.5    .045       0  6657.4      .1       0
Bank Sta=6194.5,6657.4
XS Rating Curve= 0 ,0
Exp/Cntr=0.3,0.1

Type RM Length L Ch R = 1 ,86416.1 ,1399.3,1392.1,1384.9
XS GIS Cut Line= 3
     2164460.326      338460.728     2163759.018      337667.884
     2161068.373      334558.873
#Sta/Elev= 30
       0 2309.63    90.7 2289.91   231.9 2239.95   584.7 2187.74   836.7  2138.5
   947.6 2106.94    1119 2016.16  1350.8  1877.5  1451.5 1830.81  1784.1 1811.79
  1804.2 1811.49  2046.1 1811.75  2146.9 1855.26  2247.6 1930.81  2328.3 1971.51
  2469.4 2057.16  2529.8 2111.05  2922.8 2269.96  3094.2  2283.5  3275.6 2277.12
  3477.1 2278.73  3688.7 2255.79  3880.2 2259.32  4001.1  2254.5  4172.5 2220.93
  4343.8 2254.42  4404.2 2259.79    4636 2253.49  4918.2 2268.16  5170.1 2268.07
#Mann= 3 , 0 , 0
       0      .1       0  1784.1    .045       0  2046.1      .1       0
Bank Sta=1784.1,2046.1
XS Rating Curve= 0 ,0
Exp/Cntr=0.3,0.1

Type RM Length L Ch R = 1 ,85024   ,1708.3,1705.7,1703
XS GIS Cut Line= 4
     2165849.623      337248.788     2164755.921      336376.783
     2163521.621       335659.14     2161563.495      333982.463
#Sta/Elev= 30
       0 2370.06   281.8 2338.25   382.4 2335.11   573.6 2295.22   694.4 2259.15
  1096.9 2091.82  1298.2 2030.19  1358.5 1989.56    1630 1879.12  1861.3 1823.23
  2012.1  1811.8  2032.2 1811.49  2323.8 1811.86  2434.4 1828.47    2535 1831.41
  2766.2 2008.83  2826.5 2039.12  3017.9 2095.56  3158.8  2114.8  3229.3 2115.32
    3320 2086.19  3360.2 2101.74  3440.8  2113.6  3501.2  2134.2  3662.3 2233.22
    3763 2259.03  4085.3  2261.5  4397.4 2224.66  4649.2 2246.01  5404.4 2236.96
#Mann= 3 , 0 , 0
       0      .1       0  2012.1    .045       0  2323.8      .1       0
Bank Sta=2012.1,2323.8
XS Rating Curve= 0 ,0
Exp/Cntr=0.3,0.1

Type RM Length L Ch R = 1 ,83318.3 ,2733.1,2720.1,2707.1
XS GIS Cut Line= 3
     2166566.441      335268.302      2165413.62       334780.57
      2161844.31      333132.627
#Sta/Elev= 30
       0 2236.18    80.8 2209.36   312.9 2111.73   757.1 1974.32   837.9 1962.48
  1009.5 1964.06  1090.2 1953.56  1473.5 1859.59  1685.2 1847.25  1755.8 1809.86
    1786  1807.3  1937.2 1818.16  2058.2 1808.83    2290 1810.48    2411 1835.86
  2481.6 1870.14  2521.9  1905.5  2622.7 2016.87  2965.4 2295.53    3036 2346.98
  3056.2 2355.23    3167 2355.55  3298.1 2339.13  3398.9 2304.04  3610.6 2257.22
    3792 2275.64  3892.8  2277.5  4800.1 2224.84    5042 2256.47  5183.1  2264.9
#Mann= 3 , 0 , 0
       0      .1       0  2058.2    .045       0    2290      .1       0
Bank Sta=2058.2,2290
XS Rating Curve= 0 ,0
Exp/Cntr=0.3,0.1

Type RM Length L Ch R = 1 ,80598.2 ,3531.3,3503.7,3476.2
XS GIS Cut Line= 4
     2167490.175      333154.797     2166780.747      332556.217
     2165901.352      332674.455     2162834.553      332851.812
#Sta/Elev= 30
       0 2444.86    70.6 2448.71   181.6 2443.62   272.4 2408.44   534.7 2235.41
   928.2 2029.64  1160.1 1858.07  1210.5 1828.63    1271 1804.37  1291.2 1803.58
  1442.4 1803.82  1644.1 1824.11  2047.2 1956.81  2208.3  1951.4  2359.4 1934.79
  2711.9 2052.29  2893.2 2099.48  3165.2 2215.88  3306.2 2260.59  3467.3 2231.34
  3598.2 2265.25    3699 2278.15  3819.8  2307.6    3981 2303.92    4122 2333.26
  4232.8 2332.48  4333.5 2319.25  4424.1 2322.14  4565.2 2340.89  4887.4 2332.52
#Mann= 3 , 0 , 0
       0      .1       0    1271    .045       0  1442.4      .1       0
Bank Sta=1271,1442.4
XS Rating Curve= 0 ,0
Exp/Cntr=0.3,0.1

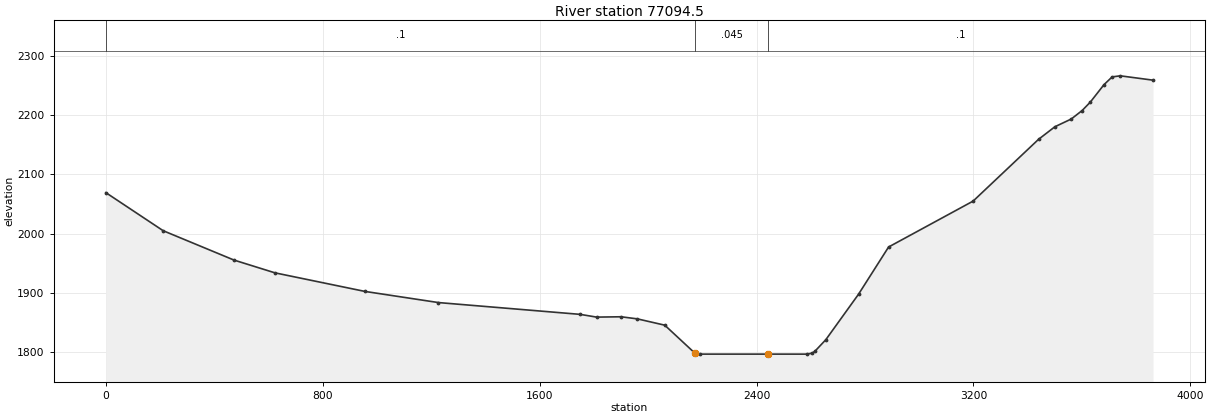
Type RM Length L Ch R = 1 ,77094.5 ,1530,1557.2,1583.9
XS GIS Cut Line= 4
     2165214.094      330664.409     2163396.184      331425.566
     2163196.657      332319.741     2162258.143      332585.776
#Sta/Elev= 30
       0 2069.27   211.2 2005.16   472.6 1955.67   623.4 1934.18   955.2 1902.87
  1226.7 1884.06  1749.6 1864.17  1809.9 1859.55  1900.4 1860.12  1960.8 1856.54
  2061.4 1845.96  2172.2 1798.93  2192.3 1797.18    2444 1797.19    2585 1797.17
  2605.1 1798.81  2615.2 1801.97  2655.4 1821.46  2776.2 1898.16    2887  1977.7
  3198.8 2055.07  3440.1 2159.16  3500.4 2180.36  3560.8 2193.41    3601 2207.73
  3631.2 2221.96  3681.5  2251.3  3711.6 2264.38  3741.8 2266.19  3862.5 2258.87
#Mann= 3 , 0 , 0
       0      .1       0  2172.2    .045       0    2444      .1       0
Bank Sta=2172.2,2444
XS Rating Curve= 0 ,0
Exp/Cntr=0.3,0.1