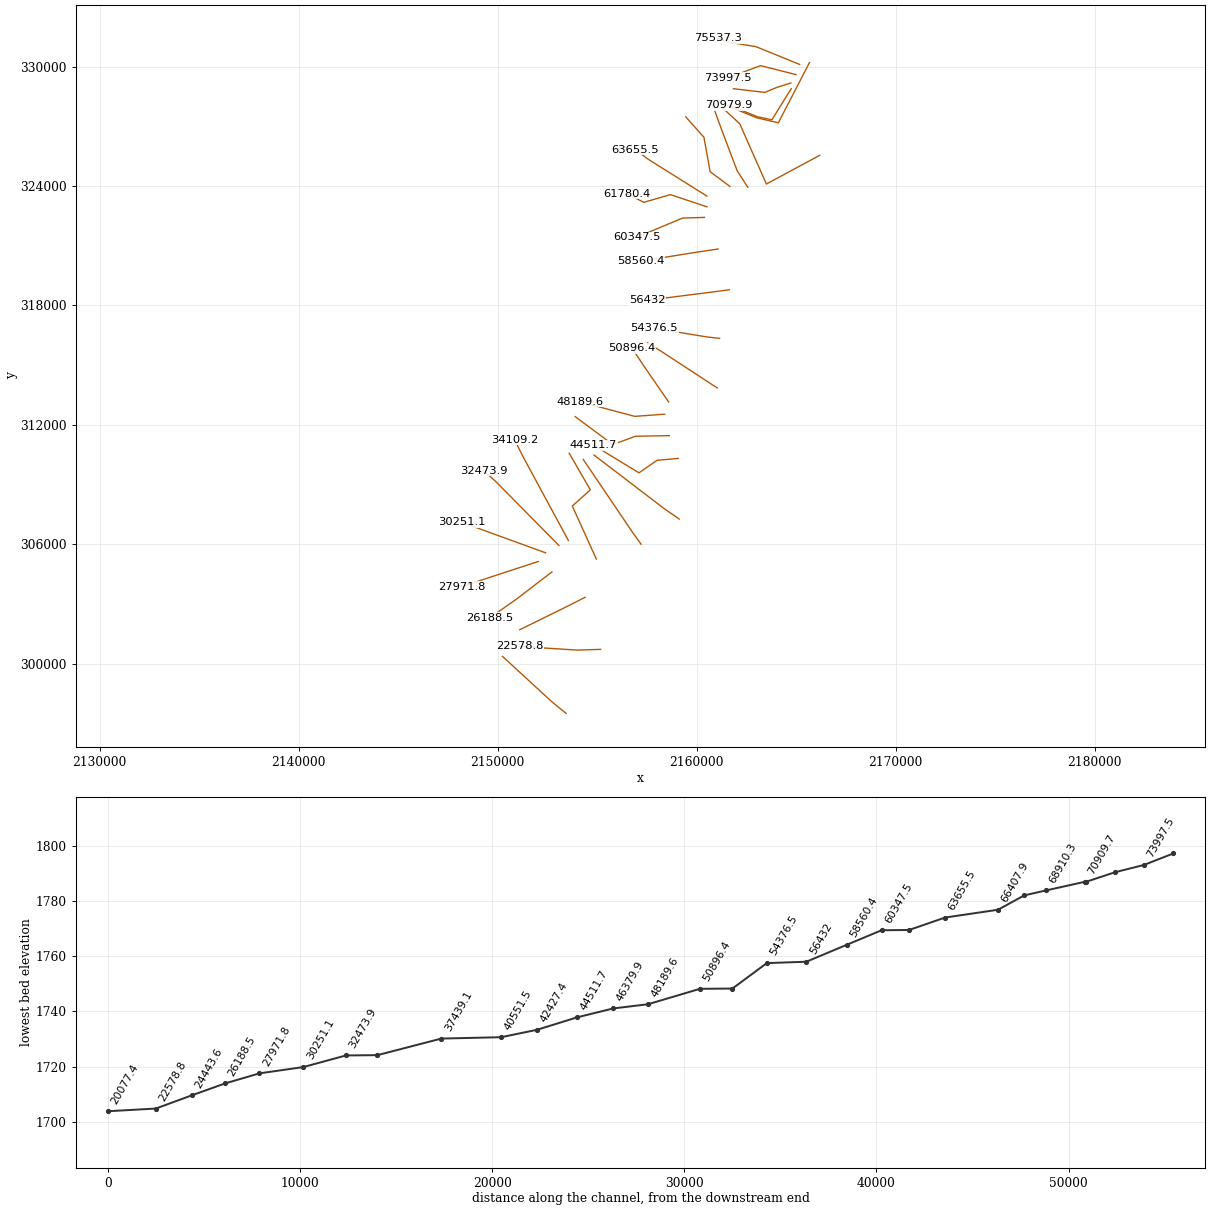
HEC-RAS study GrnbrRv.prj: GrnbrRv

--- GrnbrRv.g01 (geometry) --- (continued)

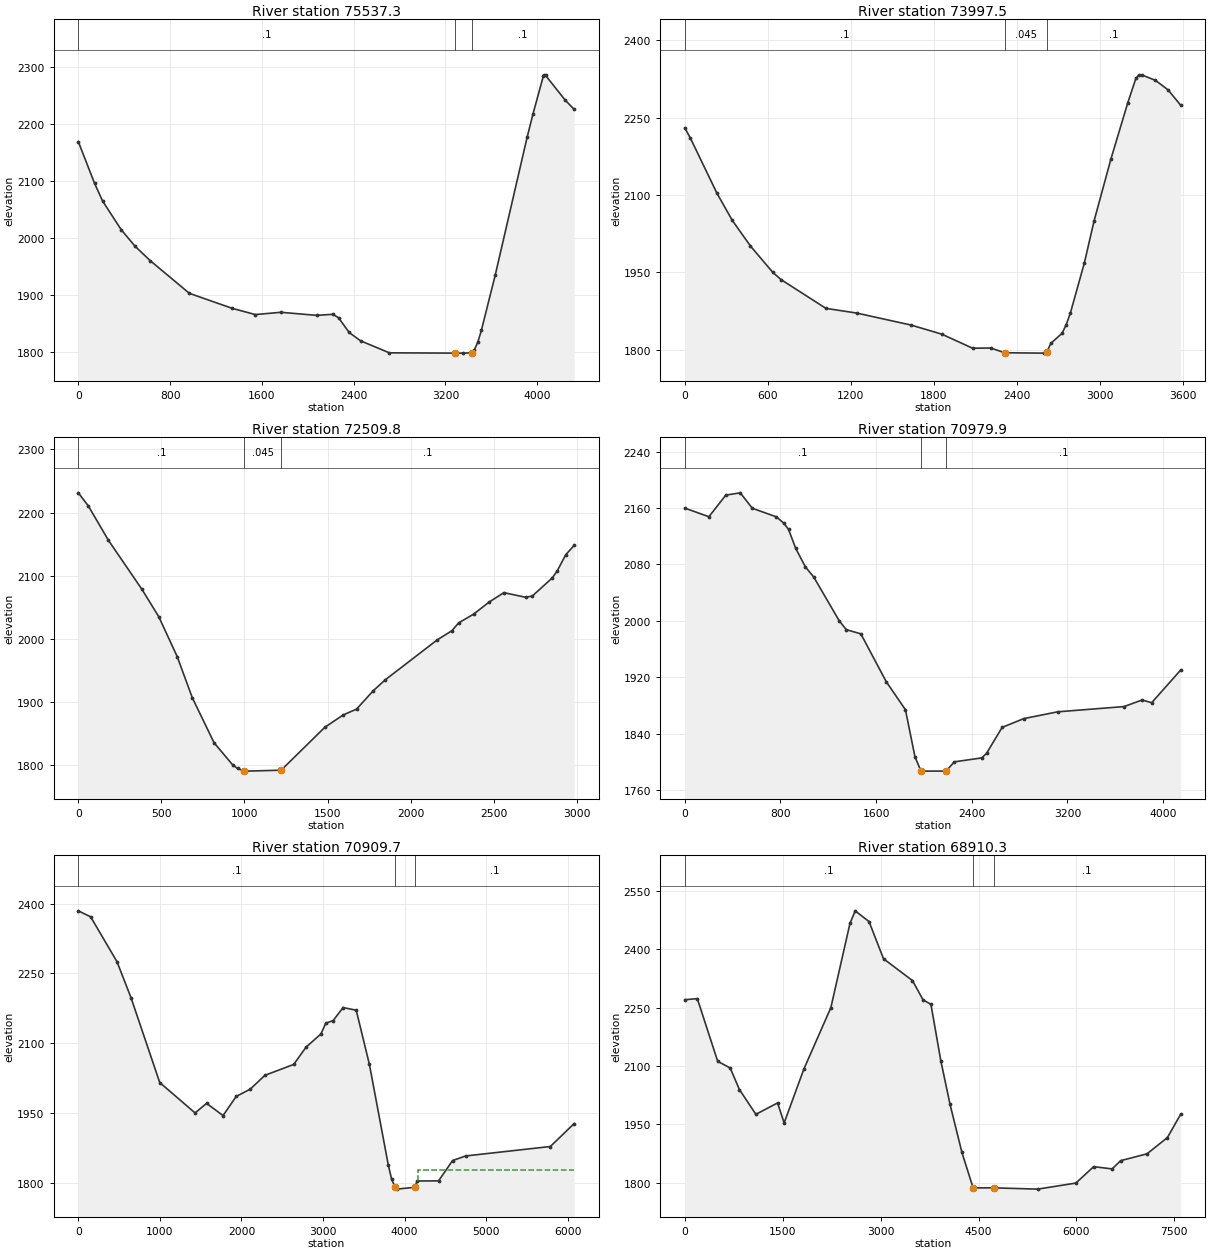
Type RM Length L Ch R = 1 ,75537.3 ,1529,1539.9,1550.7
XS GIS Cut Line= 4
     2165169.754      330110.168     2162974.961      331004.343
     2161658.968      331221.643     2161074.606      331422.517
#Sta/Elev= 30
       0 2168.56   141.2 2095.48   211.8 2064.22   373.1 2014.07   494.2 1984.96
   625.3 1959.78   968.2 1902.15  1341.3 1875.83    1543 1864.87  1764.9 1868.89
  2077.5 1863.49  2218.7 1865.34  2269.1 1859.15  2359.9 1833.52  2460.2 1818.78
  2710.9 1797.69  3282.6 1797.19  3352.8 1797.17    3433 1797.68    3453 1803.37
  3483.1 1817.05  3513.2 1837.27  3633.6 1934.03  3913.1 2177.42  3962.9 2217.15
  4052.6 2283.44  4062.6 2285.92  4072.5 2284.89    4242 2241.87  4321.7 2225.14
#Mann= 3 , 0 , 0
       0      .1       0  3282.6    .045       0    3433      .1       0
Bank Sta=3282.6,3433
XS Rating Curve= 0 ,0
Exp/Cntr=0.3,0.1

Type RM Length L Ch R = 1 ,73997.5 ,1486.2,1487.6,1488.9
XS GIS Cut Line= 3
     2164985.007      329600.267     2163204.047      330051.049
     2161570.885      329437.689
#Sta/Elev= 30
       0 2230.24    40.4 2210.38   232.2  2103.4   343.2 2050.62   474.4  2000.9
   635.9 1949.67   696.5 1935.53  1019.5 1879.87  1241.6 1870.77  1635.2 1847.42
  1857.3 1829.73  2079.1 1802.51  2210.2 1802.92  2311.1 1793.67  2593.4 1792.98
  2613.6 1794.32  2643.8 1811.87  2724.5 1831.29  2754.8 1847.81    2785  1870.6
  2885.9 1967.55  2956.4 2049.54  3077.5 2169.13  3198.5 2277.68    3259  2326.8
  3279.1 2332.51  3299.3 2333.26  3400.2 2322.51  3490.9 2304.08  3581.7 2274.36
#Mann= 3 , 0 , 0
       0      .1       0  2311.1    .045       0  2613.6      .1       0
Bank Sta=2311.1,2613.6
XS Rating Curve= 0 ,0
Exp/Cntr=0.3,0.1

Type RM Length L Ch R = 1 ,72509.8 ,1543.7,1529.9,1516.4
XS GIS Cut Line= 4
     2164726.362      329179.044     2164024.324      328957.347
     2163418.354      328706.091      2161836.92      328890.838
#Sta/Elev= 30
       0 2231.33    60.5 2210.43   181.5    2156   383.2 2078.25   484.1 2035.08
     595 1971.93   685.8 1906.84     817 1835.36     928 1800.59   958.2 1794.58
   998.6 1790.63  1008.7 1790.39  1220.6 1791.86  1482.9 1859.61  1593.8 1879.37
  1674.4  1888.6  1775.1 1917.74  1845.7  1934.7  2158.1 1997.93  2248.8  2012.9
  2289.1 2025.29  2379.8  2039.2  2470.5 2057.86  2561.2 2073.18  2692.2 2065.84
  2732.5 2067.79  2853.4 2096.68  2883.6 2108.22    2934 2133.31  2984.4 2148.08
#Mann= 3 , 0 , 0
       0      .1       0   998.6    .045       0  1220.6      .1       0
Bank Sta=998.6,1220.6
XS Rating Curve= 0 ,0
Exp/Cntr=0.3,0.1

Type RM Length L Ch R = 1 ,70979.9 ,70.6,70.3,70
XS GIS Cut Line= 4
     2164746.848      328896.623     2163773.448      327328.656
      2163042.06      327485.725     2161600.759      328064.465
#Sta/Elev= 30
       0  2159.9   201.7 2147.66   342.9 2178.32   463.9 2181.56   564.8 2159.62
   766.5 2147.45     827 2138.61   867.3 2129.81   927.8 2102.72  1008.5 2076.54
  1079.1 2061.95  1290.9 2000.21  1351.4 1987.45  1472.4 1981.56  1684.2 1913.88
  1845.5 1873.88  1925.3 1806.92  1975.2 1787.04  1985.2 1786.88  2184.7 1786.98
  2254.5 1800.04  2483.9 1805.65  2523.8 1812.16  2654.1 1848.94  2835.7 1861.39
    3118 1870.99  3672.8 1878.41    3824 1887.73  3904.7  1883.9  4146.8 1930.18
#Mann= 3 , 0 , 0
       0      .1       0  1975.2    .045       0  2184.7      .1       0
Bank Sta=1975.2,2184.7
XS Rating Curve= 0 ,0
Exp/Cntr=0.3,0.1

Type RM Length L Ch R = 1 ,70909.7 ,2020.3,1999.4,1978.1
XS GIS Cut Line= 4
     2165662.485      330206.492     2164098.272      327179.803
     2163025.383      327424.575     2161570.885      328018.833
#Sta/Elev= 30
       0 2384.57   151.2  2371.6   473.8 2275.38   645.1 2198.31   997.9 2015.84
  1431.3 1950.54  1572.5  1971.1  1774.1 1944.82  1935.3 1985.92  2106.7  2001.5
  2288.1 2031.34  2640.9 2054.72  2792.1 2091.87  2973.6 2120.06    3034 2143.24
  3124.8 2148.97  3245.7 2176.88    3407 2171.09  3568.5 2054.63  3800.7 1838.21
  3841.1 1808.18  3881.5  1791.7  3901.7 1786.88  4123.8 1790.78  4154.1 1804.32
  4416.6 1804.65    4588 1848.25  4749.2 1858.15  5786.6 1878.41  6078.7 1927.71
#Mann= 3 , 0 , 0
       0      .1       0  3881.5    .045       0  4123.8      .1       0
#XS Ineff= 2 , 0
                         4164.54         1827.95
Permanent Ineff=
       F       F
Bank Sta=3881.5,4123.8
XS Rating Curve= 0 ,0
Exp/Cntr=0.3,0.1

Type RM Length L Ch R = 1 ,68910.3 ,1136.7,1137.5,1138.3
XS GIS Cut Line= 4
     2166177.932       325545.14     2163496.888      324103.446
     2162157.502      327130.821     2161245.823      327973.255
#Sta/Elev= 30
       0 2270.15   191.5 2273.12     504 2112.06   695.5  2094.9   836.6 2039.65
  1088.6 1975.92  1421.2 2005.13    1522 1953.78  1824.4 2092.26  2237.7 2249.94
    2530 2466.02  2610.7 2498.54  2822.3 2470.92  3044.1 2375.41  3488.2 2319.41
  3649.7 2269.98  3770.8 2258.29  3922.2 2113.42  4063.5 2001.34  4245.1 1878.18
  4416.7 1786.93  4729.6  1787.1  5405.8 1783.79  5991.2 1799.35  6263.7  1841.5
  6546.3 1835.72  6677.5 1856.88  7081.1 1874.46    7394 1916.36  7595.8 1975.91
#Mann= 3 , 0 , 0
       0      .1       0  4416.7    .045       0  4729.6      .1       0
Bank Sta=4416.7,4729.6
XS Rating Curve= 0 ,0
Exp/Cntr=0.3,0.1

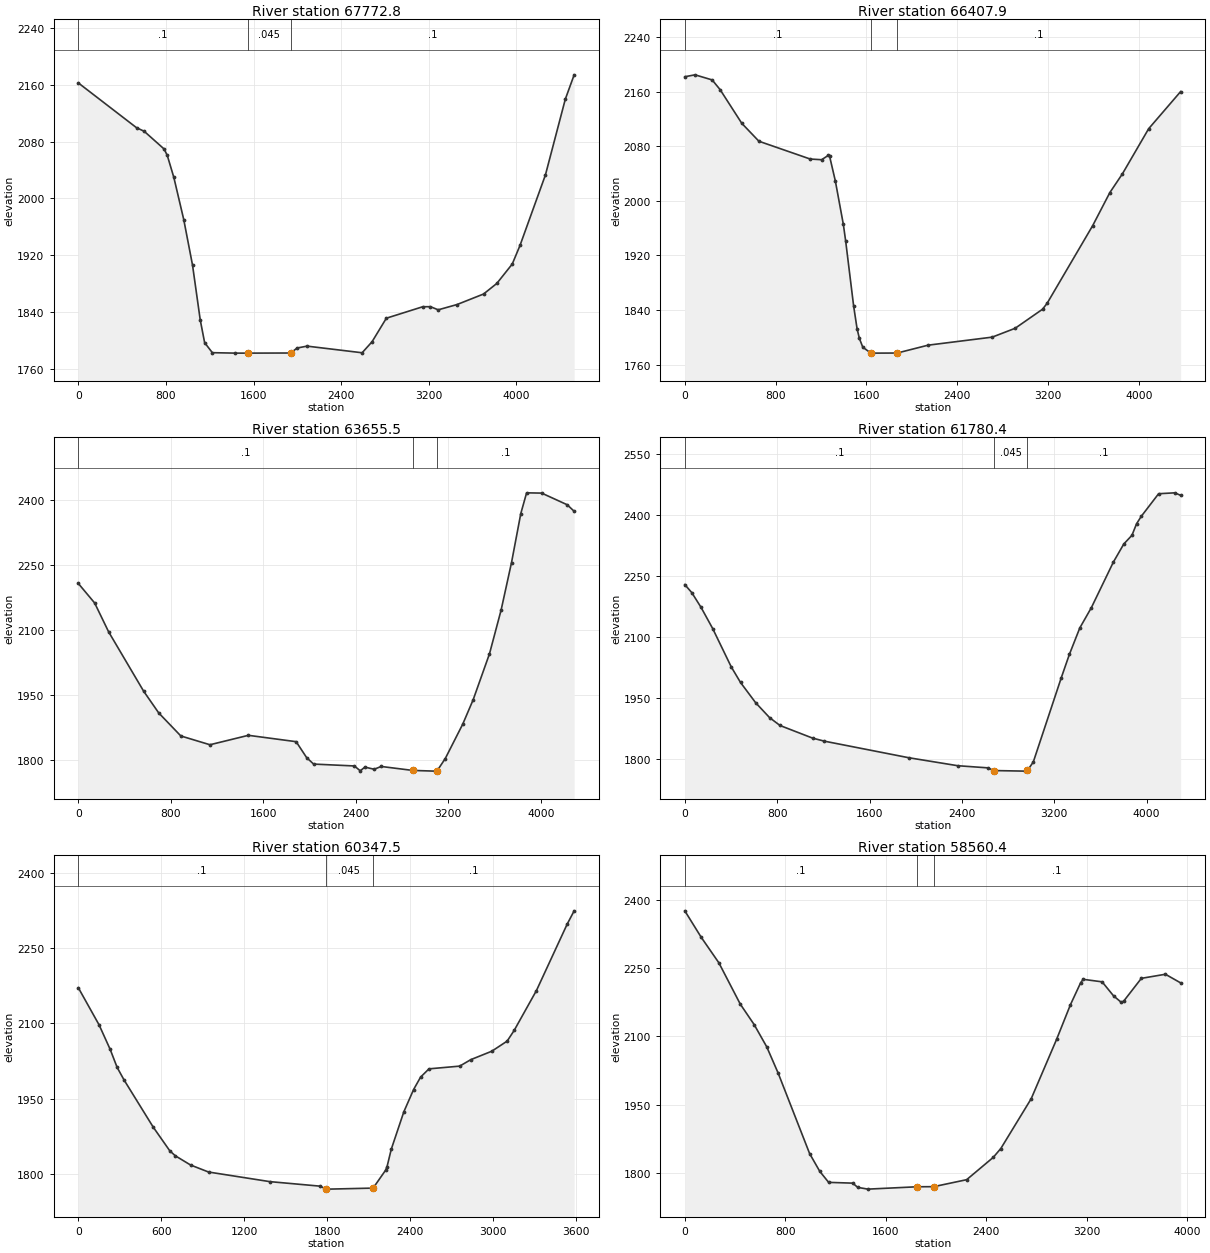
Type RM Length L Ch R = 1 ,67772.8 ,1371.3,1364.9,1358.4
XS GIS Cut Line= 4
     2162561.052      323939.043     2162026.172      324775.138
     2161291.855      326712.044     2160790.552      328087.073
#Sta/Elev= 30
       0  2162.5   531.4 2099.44   601.5  2094.4     782 2069.61   812.1 2060.49
   872.2 2029.38   962.5  1970.1  1042.8 1905.84  1113.2 1828.72  1153.4 1796.68
  1223.8 1782.62    1435 1781.99  1545.6 1781.99  1937.8 1782.16  1998.1 1789.19
  2088.6 1791.85  2591.4  1782.5  2681.9 1797.98  2812.6 1831.17  3144.7 1847.31
  3215.4 1847.39    3286 1842.98  3457.6 1850.39  3699.9 1865.21    3821 1880.09
  3962.3 1907.47    4033 1933.63  4265.1  2032.9  4446.8 2139.65  4527.5 2173.92
#Mann= 3 , 0 , 0
       0      .1       0  1545.6    .045       0  1937.8      .1       0
Bank Sta=1545.6,1937.8
XS Rating Curve= 0 ,0
Exp/Cntr=0.3,0.1

Type RM Length L Ch R = 1 ,66407.9 ,2732.9,2752.4,2771.7
XS GIS Cut Line= 4
     2161659.563      323983.961      2160669.32      324722.948
     2160359.057      326450.538       2159442.6      327479.372
#Sta/Elev= 30
       0 2181.67    90.4 2184.46   241.1 2176.99   311.4 2162.72   502.3 2113.39
     653 2087.18    1105 2061.11  1205.4  2060.1  1265.8  2066.6  1275.9 2065.09
  1326.4 2029.01    1397 1965.34  1417.2 1941.17  1487.8 1845.54    1518 1812.43
  1538.2 1798.34  1568.5 1785.38  1639.1 1776.92  1659.3 1776.79  1871.1 1776.92
  2143.5 1788.44  2708.4 1800.21  2910.1 1813.14  3151.7 1841.06    3192 1849.68
  3594.2 1963.66  3745.1 2011.99  3855.7 2039.42    4087 2105.52  4368.6  2159.9
#Mann= 3 , 0 , 0
       0      .1       0  1639.1    .045       0  1871.1      .1       0
Bank Sta=1639.1,1871.1
XS Rating Curve= 0 ,0
Exp/Cntr=0.3,0.1

Type RM Length L Ch R = 1 ,63655.5 ,1856.1,1875.1,1894.1
XS GIS Cut Line= 3
     2160506.742      323496.229     2157528.622      325365.867
     2156915.457      325835.609
#Sta/Elev= 30
       0 2206.83   141.1 2161.88     262  2095.3   564.2 1958.69   695.2 1908.29
   886.6  1855.1  1138.5 1834.83    1471 1856.58  1884.1 1841.91  1974.8 1805.13
  2035.2 1790.25  2387.9  1785.9  2438.3 1774.71  2478.6 1783.23  2559.2  1778.3
  2619.6 1784.74  2891.7  1775.6  3083.1 1773.98  3103.3 1774.72  3173.8 1802.95
  3324.9 1882.26  3415.6 1938.94  3556.5 2044.74  3656.8 2145.35  3747.1 2255.22
  3827.3 2368.26  3877.5 2415.96  4007.9 2415.32  4228.6 2388.45  4288.8 2373.38
#Mann= 3 , 0 , 0
       0      .1       0  2891.7    .045       0  3103.3      .1       0
Bank Sta=2891.7,3103.3
XS Rating Curve= 0 ,0
Exp/Cntr=0.3,0.1

Type RM Length L Ch R = 1 ,61780.4 ,1430.3,1432.9,1435.5
XS GIS Cut Line= 4
     2160514.132      322956.768     2158672.396      323569.158
     2157337.122      323182.632      2156479.26      323621.857
#Sta/Elev= 30
       0 2227.93    60.3 2208.31   140.8 2171.96   241.4 2119.98   402.3 2025.71
   482.7 1987.36   613.4  1937.7   734.1 1901.07   824.6 1881.66  1106.2  1850.7
  1206.8 1843.26  1940.9 1802.36    2364 1782.79  2625.8  1777.5  2676.2 1770.88
  2948.2 1769.48  2968.3 1771.13  3018.7 1792.07  3260.5 1998.65    3331 2056.26
  3421.3 2121.36  3521.7 2171.38  3712.5 2283.45  3802.8 2327.88  3873.1 2349.11
  3913.2 2377.52  3953.4 2395.57    4104 2451.27  4244.5  2453.5  4294.7 2447.32
#Mann= 3 , 0 , 0
       0      .1       0  2676.2    .045       0  2968.3      .1       0
Bank Sta=2676.2,2968.3
XS Rating Curve= 0 ,0
Exp/Cntr=0.3,0.1

Type RM Length L Ch R = 1 ,60347.5 ,1793.1,1787.1,1781.1
XS GIS Cut Line= 3
     2160388.504      322424.697     2159287.324      322392.009
     2156996.551      321434.453
#Sta/Elev= 30
       0 2171.05   150.2 2096.91   230.4 2047.99   280.4 2012.23   330.5 1987.13
   540.8  1893.3     661 1845.87   701.1 1835.88   811.2 1817.52   941.4 1803.49
  1384.3 1784.34  1747.6 1775.31    1788 1769.99  1808.2 1769.38  2131.1 1771.42
    2222 1807.38  2232.1 1814.46  2262.4 1849.01  2353.2 1923.62  2423.8 1968.06
  2474.3 1992.82  2534.9 2009.29  2756.9 2014.74  2837.6 2027.68    2989 2044.47
  3100.1 2064.65  3150.5 2085.81    3312 2165.57    3534 2297.93  3584.5  2324.5
#Mann= 3 , 0 , 0
       0      .1       0    1788    .045       0  2131.1      .1       0
Bank Sta=1788,2131.1
XS Rating Curve= 0 ,0
Exp/Cntr=0.3,0.1

Type RM Length L Ch R = 1 ,58560.4 ,2128.6,2128.4,2128.2
XS GIS Cut Line= 3
     2161068.373      320835.873     2160115.079      320695.466
     2157169.404      320223.195
#Sta/Elev= 30
       0 2376.47   130.5 2318.32     271 2262.19   441.6 2171.24     552 2126.24
   652.4 2077.16   742.8  2019.7   993.8 1842.26  1074.4 1803.33    1145 1779.07
  1336.5 1777.36  1376.8 1768.03  1457.4 1764.19  1850.5 1769.39  1981.5  1769.6
  2243.6 1784.95  2455.2 1834.02  2515.7 1853.56  2757.6 1963.17  2959.2 2093.43
    3070 2170.07  3150.7 2218.02  3170.8 2225.78    3322 2220.24  3412.7  2189.5
  3473.2 2175.41  3493.3 2177.66  3634.4 2227.93  3825.9 2236.93  3946.9 2217.96
#Mann= 3 , 0 , 0
       0      .1       0  1850.5    .045       0  1981.5      .1       0
Bank Sta=1850.5,1981.5
XS Rating Curve= 0 ,0
Exp/Cntr=0.3,0.1

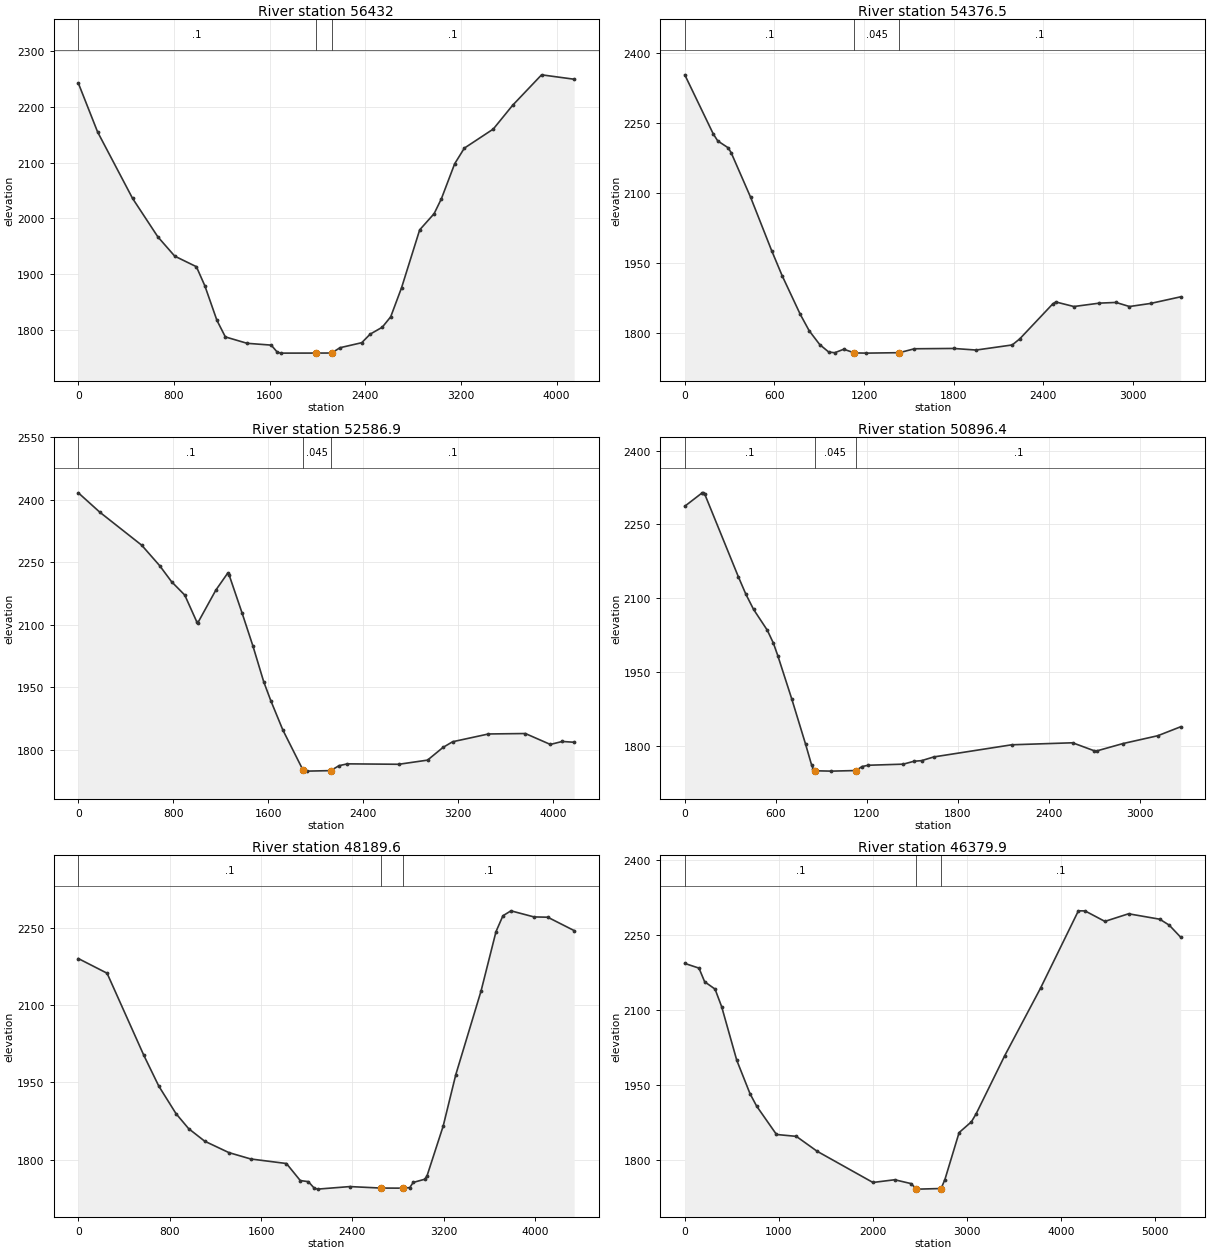
Type RM Length L Ch R = 1 ,56432   ,2067.7,2055.5,2045
XS GIS Cut Line= 3
     2161632.432      318786.979     2160573.251       318648.47
     2157518.267      318262.634
#Sta/Elev= 30
       0 2242.49   161.2 2154.87   453.5 2035.75   665.1 1966.69   806.2 1932.08
   987.6 1913.09  1058.1 1878.91  1159.1 1816.92  1229.7 1787.11  1411.5 1775.63
  1613.4 1772.38  1663.9 1759.76  1694.2    1758  1986.9  1758.1  2118.2 1758.19
  2188.8  1767.7  2370.6 1776.71  2441.2 1792.08  2542.2 1804.48  2612.9 1823.21
  2703.7 1875.38  2855.2 1979.18  2976.3 2008.36  3036.9 2035.06    3148 2097.83
  3228.7 2125.83    3471 2160.12  3632.6 2202.74  3874.9 2257.41  4147.4 2249.51
#Mann= 3 , 0 , 0
       0      .1       0  1986.9    .045       0  2118.2      .1       0
Bank Sta=1986.9,2118.2
XS Rating Curve= 0 ,0
Exp/Cntr=0.3,0.1

Type RM Length L Ch R = 1 ,54376.5 ,1793.6,1789.6,1783.9
XS GIS Cut Line= 3
     2161142.272      316350.218     2160514.132      316416.727
     2157861.167       316852.73
#Sta/Elev= 30
       0 2352.35   190.5 2226.09   220.6 2211.08   290.8 2196.32   310.8 2185.67
   441.2 2090.28   581.5 1976.67   651.8 1923.05   772.6 1840.76     833 1805.33
   903.5 1775.81   963.9 1759.81  1004.2 1758.38  1064.6 1765.82  1135.1 1758.02
  1215.7  1757.5  1437.2 1758.48  1537.9 1766.82  1799.7  1767.5  1950.8 1764.08
  2192.4 1774.98  2242.8 1787.92  2464.3 1862.84  2484.4 1866.87  2605.3 1857.12
  2776.4 1864.37  2887.2 1865.84  2977.8 1857.13  3118.8 1863.68  3320.2 1877.85
#Mann= 3 , 0 , 0
       0      .1       0  1135.1    .045       0  1437.2      .1       0
Bank Sta=1135.1,1437.2
XS Rating Curve= 0 ,0
Exp/Cntr=0.3,0.1

Type RM Length L Ch R = 1 ,52586.9 ,1699.3,1690.5,1681.7
XS GIS Cut Line= 3
     2161028.849       313855.34     2158193.711      315707.299
     2157517.639      316120.485
#Sta/Elev= 30
       0 2416.48   181.4 2369.91   534.2 2290.71   685.3 2241.67   786.1    2203
     897 2170.97   997.8 2106.99  1007.9 2104.83    1159 2182.97  1259.8 2224.05
  1269.9 2220.09  1380.8 2127.26  1471.5 2048.69  1562.2 1963.05  1622.6 1917.09
  1723.4 1847.21  1894.8 1750.01    1925  1748.3  2126.6 1749.52  2197.1 1761.38
  2267.7 1765.77  2701.1 1764.76    2943 1774.72    3074 1805.34  3154.6 1818.88
  3456.6 1837.52  3767.5 1838.58  3978.2 1812.35  4078.4 1819.52  4178.7  1817.6
#Mann= 3 , 0 , 0
       0      .1       0  1894.8    .045       0  2126.6      .1       0
Bank Sta=1894.8,2126.6
XS Rating Curve= 0 ,0
Exp/Cntr=0.3,0.1

Type RM Length L Ch R = 1 ,50896.4 ,2690.5,2706.8,2723.1
XS GIS Cut Line= 3
     2158585.375      313150.402     2157373.435      314909.193
     2156744.787      315852.405
#Sta/Elev= 30
       0 2287.02   110.8 2313.33   120.9 2314.25     131 2311.97   352.6 2143.92
     403 2107.81   453.4 2077.23     544  2034.8   584.4 2008.37   614.6 1981.77
   705.3    1895   795.9 1803.55   836.2 1760.54   846.3 1752.81   856.4 1748.92
   967.2  1748.2  1128.4  1749.4  1168.7 1757.51    1209 1760.15  1440.7 1762.39
  1511.3 1768.27  1561.6 1769.54  1642.2  1777.1    2156 1801.77  2557.2 1805.85
  2697.7 1789.83  2717.7 1789.41  2888.2 1804.19    3119 1820.23  3269.4 1838.41
#Mann= 3 , 0 , 0
       0      .1       0   856.4    .045       0  1128.4      .1       0
Bank Sta=856.4,1128.4
XS Rating Curve= 0 ,0
Exp/Cntr=0.3,0.1

Type RM Length L Ch R = 1 ,48189.6 ,1796.5,1809.7,1822.9
XS GIS Cut Line= 4
     2158385.848      312537.042     2156880.381      312426.541
     2155222.981      312869.587     2154144.059      313157.792
#Sta/Elev= 30
       0  2190.3   251.6 2161.84   573.6 2002.39   704.4 1942.72   855.4 1889.19
   966.1 1860.02    1107 1835.64  1318.3 1813.55  1509.5 1801.17  1822.4 1792.35
  1943.5 1759.28  2014.1 1757.14  2064.6 1744.85  2094.8 1742.62  2377.4 1747.57
  2649.9 1744.69  2841.6  1744.5  2902.2 1745.58  2932.4 1755.59  3033.4 1761.82
  3053.6 1768.46  3194.8 1864.93  3305.6 1965.07  3526.9 2127.57  3657.7 2242.69
  3718.1 2273.35  3788.5 2282.95  3989.7 2271.13  4110.5 2270.56  4341.9 2244.59
#Mann= 3 , 0 , 0
       0      .1       0  2649.9    .045       0  2841.6      .1       0
Bank Sta=2649.9,2841.6
XS Rating Curve= 0 ,0
Exp/Cntr=0.3,0.1

Type RM Length L Ch R = 1 ,46379.9 ,1862.1,1868.2,1874.3
XS GIS Cut Line= 4
     2158624.619      311458.606     2156915.457      311428.712
     2155781.738       311008.57     2153889.929      312414.288
#Sta/Elev= 30
       0 2192.37   150.8    2183   211.2 2155.71   321.8 2141.06   392.2 2105.83
     553 1998.68   693.8 1931.97   764.2 1907.13   975.4 1850.36  1186.5  1846.6
  1407.8 1816.84  2001.6 1754.42  2233.4 1759.84  2404.6 1752.27  2465.1 1741.64
  2485.2  1741.1    2727 1742.34  2767.4 1760.29  2918.5 1854.16  3049.4 1875.71
  3099.8 1891.71    3402 2007.25  3784.7 2142.86  4187.6 2297.55  4258.1 2297.42
  4469.6 2276.44  4721.4 2291.65  5053.8 2280.77  5154.5 2268.88  5275.4 2244.88
#Mann= 3 , 0 , 0
       0      .1       0  2465.1    .045       0    2727      .1       0
Bank Sta=2465.1,2727
XS Rating Curve= 0 ,0
Exp/Cntr=0.3,0.1

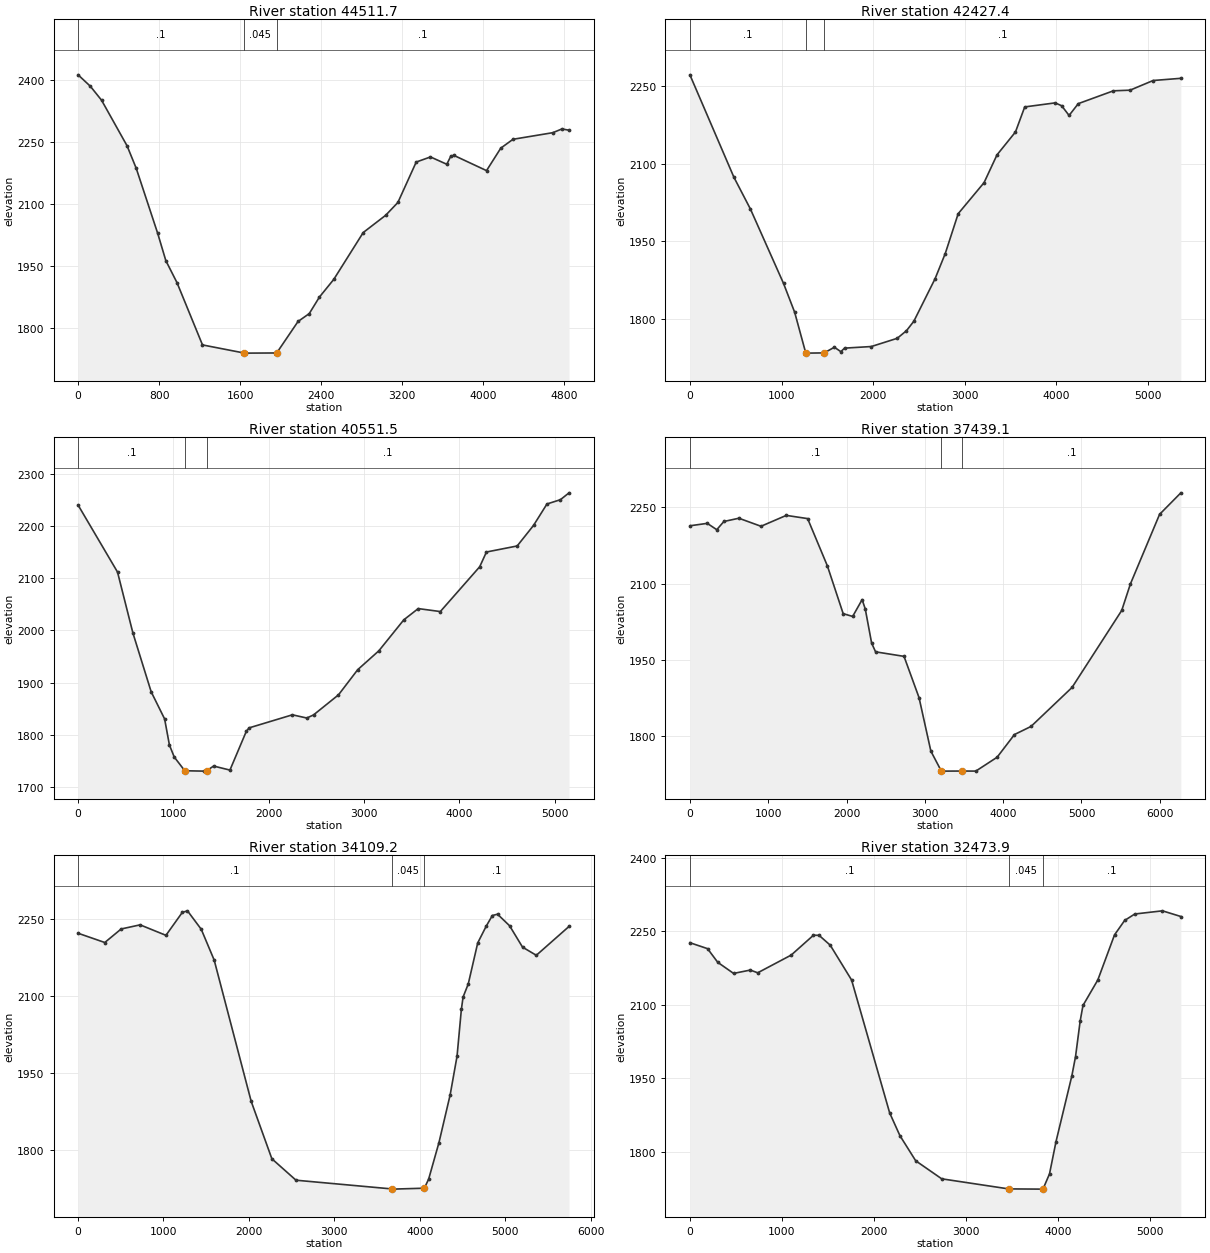
Type RM Length L Ch R = 1 ,44511.7 ,2112.7,2084.3,2056
XS GIS Cut Line= 4
     2159066.127      310312.279     2158001.985      310220.316
     2157095.493      309589.713     2154809.558      310982.294
#Sta/Elev= 30
       0 2413.45   120.9 2385.73   231.8 2351.83   483.7 2241.13   574.4 2186.37
     786 2028.83   866.6 1962.46   977.4 1908.68  1228.7 1757.81  1640.3 1738.14
  1660.4  1737.9  1961.6 1738.29  2172.4 1814.74  2283.1 1833.84  2383.7 1874.05
  2524.6 1916.68  2816.4  2030.7  3037.8 2072.49  3158.5 2103.61  3339.6 2201.74
  3480.5 2214.12  3641.5 2196.36  3681.8 2216.26    3712 2217.87    4034 2180.92
  4174.9 2235.52  4295.6 2256.98  4688.1 2272.99  4778.6 2282.05  4849.1 2279.03
#Mann= 3 , 0 , 0
       0      .1       0  1640.3    .045       0  1961.6      .1       0
Bank Sta=1640.3,1961.6
XS Rating Curve= 0 ,0
Exp/Cntr=0.3,0.1

Type RM Length L Ch R = 1 ,42427.4 ,1882.9,1875.9,1868.2
XS GIS Cut Line= 3
     2159118.677      307264.366     2158338.577      307809.418
     2154835.834      310483.067
#Sta/Elev= 30
       0 2272.41   480.8 2073.87   661.2 2012.23  1022.2 1868.26  1143.2  1812.6
  1264.2 1733.78  1274.3  1733.4  1465.9 1733.86  1576.8 1744.83  1647.4 1736.23
  1687.8 1743.07  1980.2 1746.18  2262.5 1762.09  2363.4 1776.76    2444 1795.14
    2676  1877.6  2786.9 1926.31    2928 2003.48  3210.4 2063.61  3351.6 2117.39
  3553.2 2161.75  3654.1 2210.24  3986.8 2218.09  4057.4 2212.49  4138.1 2193.73
  4238.9 2216.62  4622.1 2241.45  4803.6 2242.68  5055.7 2261.41  5358.2 2265.66
#Mann= 3 , 0 , 0
       0      .1       0  1264.2    .045       0  1465.9      .1       0
Bank Sta=1264.2,1465.9
XS Rating Curve= 0 ,0
Exp/Cntr=0.3,0.1

Type RM Length L Ch R = 1 ,40551.5 ,3144.9,3112.5,3080
XS GIS Cut Line= 3
     2157200.594       306003.16      2156793.33      306568.075
     2154297.194      310259.729
#Sta/Elev= 30
       0 2239.66   413.8 2111.53   575.3 1994.94     767 1882.47   908.1 1830.52
   958.6 1780.62    1009 1757.71  1119.9 1731.42  1321.5  1730.7  1351.8 1731.76
  1422.3 1740.39  1593.7 1732.69  1765.1 1806.64  1795.4 1813.48  2249.1 1838.43
  2400.3  1832.3  2470.9 1838.21    2733 1876.64  2934.7 1924.77  3156.5 1960.87
  3418.6 2020.15  3569.8 2041.64  3801.7 2035.96  4215.1  2121.7  4285.7 2149.88
  4608.3 2161.44  4779.7 2200.71  4920.9 2241.75    5062 2249.96  5152.8  2263.1
#Mann= 3 , 0 , 0
       0      .1       0  1119.9    .045       0  1351.8      .1       0
Bank Sta=1119.9,1351.8
XS Rating Curve= 0 ,0
Exp/Cntr=0.3,0.1

Type RM Length L Ch R = 1 ,37439.1 ,3299.7,3329.9,3360
XS GIS Cut Line= 4
     2154953.124      305256.049     2153745.416      307921.244
     2154651.908      308735.772     2153587.766       310575.03
#Sta/Elev= 30
       0  2213.8     222  2218.6   343.1 2206.09   433.9 2222.28   625.6 2228.69
   908.1 2212.84    1231  2234.3  1503.4 2227.97  1755.6 2134.77  1957.4 2040.58
  2078.5 2035.14  2199.6 2068.32    2240 2049.45  2320.7 1982.51  2371.1 1965.35
  2734.4 1956.42  2926.1 1875.12  3077.1 1769.68  3208.1 1731.04  3228.2 1730.21
    3480  1730.4  3651.2 1730.26  3923.2  1757.6  4144.7 1802.31  4356.2 1818.29
  4879.9 1895.13  5514.4 2046.91  5625.1  2099.1  5997.8 2236.33  6269.7 2278.77
#Mann= 3 , 0 , 0
       0      .1       0  3208.1    .045       0    3480      .1       0
Bank Sta=3208.1,3480
XS Rating Curve= 0 ,0
Exp/Cntr=0.3,0.1

Type RM Length L Ch R = 1 ,34109.2 ,1628.8,1635.2,1641.6
XS GIS Cut Line= 3
     2153548.353      306187.086     2151288.693      310364.829
     2150842.016      311258.183
#Sta/Elev= 30
       0 2222.59   312.6 2204.55   504.2 2230.89   726.1 2238.93  1028.6 2218.52
  1220.2 2263.18  1280.7 2266.25    1442 2230.29  1593.3 2170.39  2026.9 1895.04
    2269 1783.29  2551.3 1741.59  3670.7 1724.63  3680.8 1724.21  4053.9 1726.02
  4104.3 1743.57  4225.3 1814.91  4356.4 1907.85  4437.1 1983.23  4487.5 2074.11
  4507.7 2098.34  4568.2 2123.77  4679.1 2203.77    4780 2236.84  4850.6 2257.13
  4911.1  2259.7  5052.4 2237.12  5203.7 2195.55  5365.1 2179.64  5748.5 2235.89
#Mann= 3 , 0 , 0
       0      .1       0  3670.7    .045       0  4053.9      .1       0
Bank Sta=3670.7,4053.9
XS Rating Curve= 0 ,0
Exp/Cntr=0.3,0.1

Type RM Length L Ch R = 1 ,32473.9 ,2212.9,2222.9,2232.8
XS GIS Cut Line= 3
     2153075.401      305937.472     2149882.974      309169.311
     2149291.784      309694.814
#Sta/Elev= 30
       0 2226.57   191.8 2214.44   302.8 2186.54   474.5 2163.97   656.2 2170.78
   736.9 2165.24  1100.4 2201.34  1342.6 2241.87  1403.2 2241.61  1524.3 2221.58
  1756.5 2150.54  2170.4 1879.46  2281.5  1833.2  2453.1 1781.91  2735.7 1745.12
  3462.6 1724.58    3826 1724.11  3836.1 1724.28  3906.8 1755.23  3977.4 1821.12
    4149 1954.73  4189.4  1994.3  4239.9 2067.06  4270.2 2098.62  4431.7 2150.69
  4612.8 2242.49    4723    2272  4833.1  2285.1  5133.5 2291.58  5333.7    2280
#Mann= 3 , 0 , 0
       0      .1       0  3462.6    .045       0  3836.1      .1       0
Bank Sta=3462.6,3836.1
XS Rating Curve= 0 ,0
Exp/Cntr=0.3,0.1

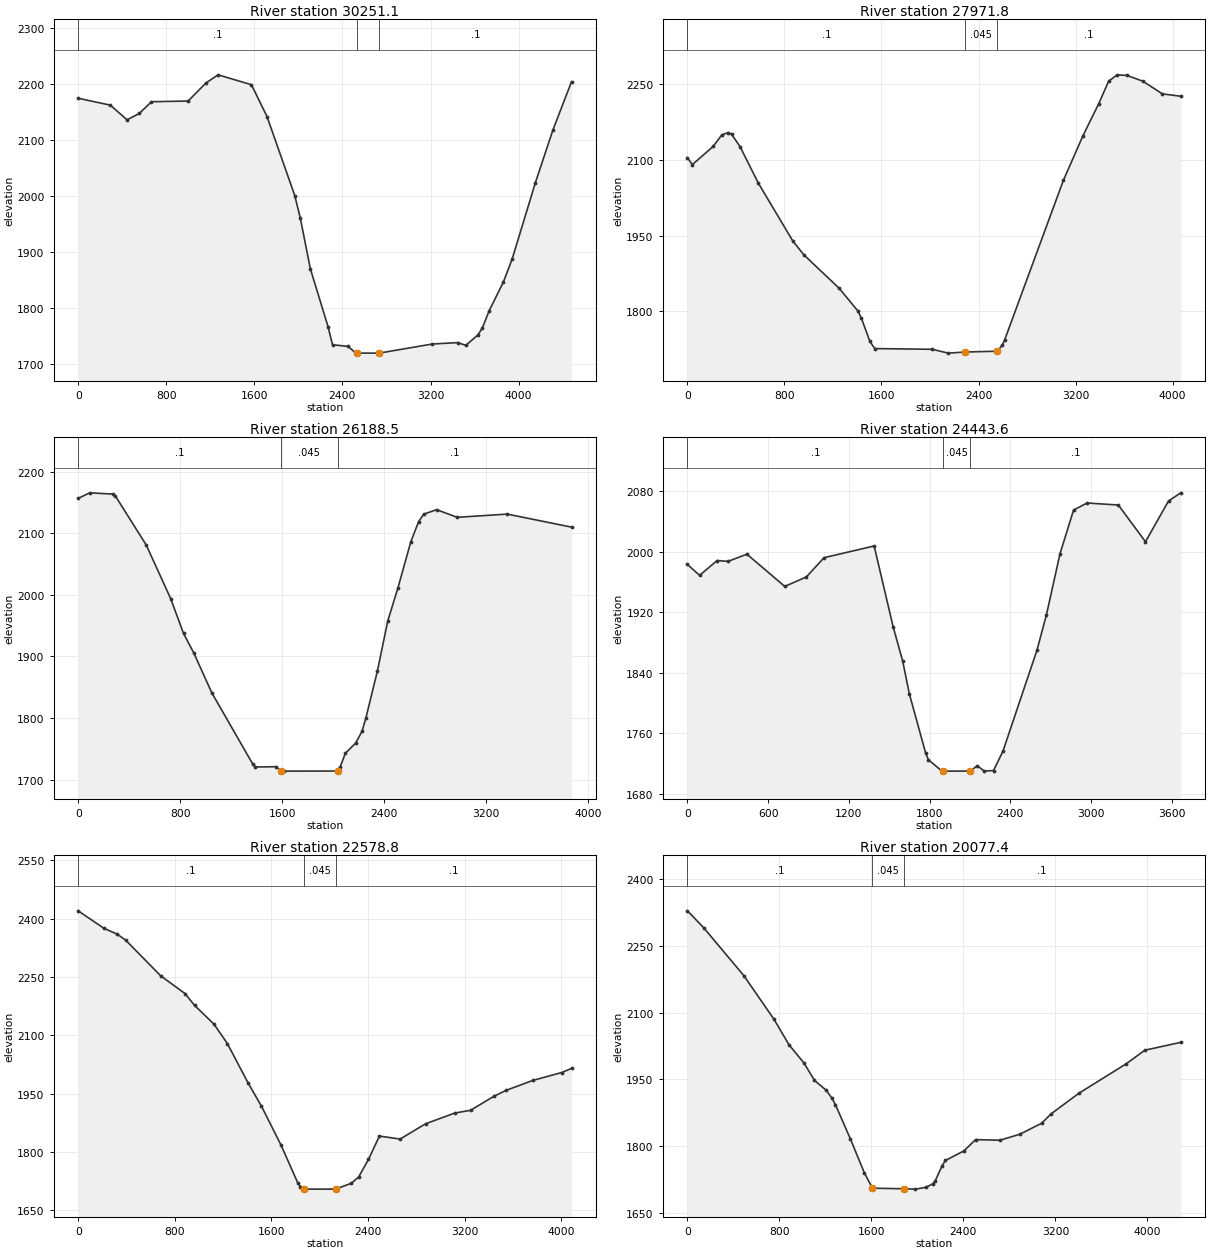
Type RM Length L Ch R = 1 ,30251.1 ,2265,2279.2,2293.4
XS GIS Cut Line= 3
     2152405.385      305569.621      2148831.97      306870.239
     2148201.367      307119.852
#Sta/Elev= 30
       0 2175.19   292.5 2162.84   443.8 2136.61   554.8 2148.05   665.7 2169.02
   998.6 2170.24    1160 2202.47    1271 2217.06  1573.6 2199.36  1714.8 2142.59
  1966.9 2001.45  2017.4 1961.08  2108.2 1870.84  2269.6 1766.94  2309.9 1734.88
  2451.1 1731.89  2521.7  1719.9  2531.8  1719.9  2733.5  1719.9  3217.7 1736.22
  3449.7  1738.7  3520.3 1733.64  3631.3 1752.49  3671.6 1765.04  3732.1 1795.26
  3862.6  1847.2  3942.4  1888.4  4151.8 2023.89  4311.4 2118.22    4481 2204.85
#Mann= 3 , 0 , 0
       0      .1       0  2531.8    .045       0  2733.5      .1       0
Bank Sta=2531.8,2733.5
XS Rating Curve= 0 ,0
Exp/Cntr=0.3,0.1

Type RM Length L Ch R = 1 ,27971.8 ,1775.1,1783.4,1791.6
XS GIS Cut Line= 3
     2152037.534      305136.081     2149226.096      304216.452
     2148175.092      303861.738
#Sta/Elev= 30
       0 2103.93    40.4 2090.16     212 2126.16   282.7 2148.74   333.2 2153.49
   363.4 2150.55   434.1 2125.68   585.6 2053.22   868.2 1939.56   959.1 1912.15
  1251.9 1845.58  1403.3 1801.58  1433.6 1787.17  1504.2 1740.93  1544.6 1726.63
  2019.1 1725.19  2150.4 1717.63  2291.7 1719.84  2554.2  1721.4  2594.6 1732.98
  2614.8 1743.31  3099.2 2058.84  3260.5 2147.04  3391.6  2210.9  3472.3 2254.96
  3542.9  2267.7  3623.6 2266.56  3754.7  2255.1    3916 2230.05  4067.3 2225.37
#Mann= 3 , 0 , 0
       0      .1       0  2291.7    .045       0  2554.2      .1       0
Bank Sta=2291.7,2554.2
XS Rating Curve= 0 ,0
Exp/Cntr=0.3,0.1

Type RM Length L Ch R = 1 ,26188.5 ,1748.5,1744.9,1740.7
XS GIS Cut Line= 3
     2152720.687      304610.579     2150920.841      303231.135
     2149607.086      302311.506
#Sta/Elev= 30
       0 2156.57    90.7 2165.53   272.1  2163.5   292.3 2160.21   534.2 2080.72
   725.6 1993.92   826.4 1937.37   907.1 1905.75  1048.2 1841.13  1370.7  1725.1
  1390.8 1720.71  1552.1 1721.16  1592.4 1714.55  1612.6    1714  2035.9 1714.17
    2056 1720.81  2096.3 1742.98    2177 1759.38  2227.4  1778.6  2257.6 1800.31
  2348.4 1876.84    2429  1957.5  2509.7 2011.76  2610.6 2086.45  2671.1 2118.64
  2711.4 2130.87  2812.3  2138.2  2973.7 2125.81    3367 2131.01  3871.3 2109.87
#Mann= 3 , 0 , 0
       0      .1       0  1592.4    .045       0  2035.9      .1       0
Bank Sta=1592.4,2035.9
XS Rating Curve= 0 ,0
Exp/Cntr=0.3,0.1

Type RM Length L Ch R = 1 ,24443.6 ,1876.2,1864.8,1854
XS GIS Cut Line= 3
     2154389.157      303336.236     2153430.115      302850.146
     2151104.767      301707.179
#Sta/Elev= 30
       0 1983.18    90.4 1968.82   221.1 1988.39   301.5 1987.27   442.1 1996.78
   723.5 1954.12   884.3 1966.71  1014.9 1992.12  1387.7 2007.65  1528.9  1900.7
  1599.5 1855.55  1649.9 1811.57  1770.8 1733.32    1791 1724.75  1891.8 1709.66
  1901.9 1709.66  2103.6 1709.73    2154 1716.89  2204.4  1709.8    2275 1710.41
  2345.5 1736.34  2597.6 1869.61  2668.2 1916.65    2769 1997.46  2869.8 2055.18
  2970.6 2064.54  3202.5 2061.85  3404.1 2013.26  3575.5 2067.24  3666.3    2078
#Mann= 3 , 0 , 0
       0      .1       0  1901.9    .045       0  2103.6      .1       0
Bank Sta=1901.9,2103.6
XS Rating Curve= 0 ,0
Exp/Cntr=0.3,0.1

Type RM Length L Ch R = 1 ,22578.8 ,2516.8,2501.4,2485.8
XS GIS Cut Line= 3
     2155169.509      300719.537      2153995.03      300682.449
      2151091.63      300866.375
#Sta/Elev= 30
       0 2420.29   210.9 2375.71   321.4 2360.44   391.7 2345.27   682.9 2253.27
   883.8 2207.72   964.2 2177.08  1124.8 2128.74  1235.5 2078.87  1406.6 1977.75
  1517.3 1918.07  1678.4 1818.57  1819.3  1719.9  1839.4 1711.55  1869.6 1705.57
  1889.8  1704.9  2131.4 1704.99  2262.2 1720.01  2322.6 1736.49  2403.2 1781.32
  2493.8 1841.29  2664.9 1833.55  2876.3 1872.93  3117.9 1900.48  3248.8 1907.59
    3440 1943.25  3540.7 1958.54  3762.2 1984.19  4003.8 2004.69  4084.3 2015.23
#Mann= 3 , 0 , 0
       0      .1       0  1869.6    .045       0  2131.4      .1       0
Bank Sta=1869.6,2131.4
XS Rating Curve= 0 ,0
Exp/Cntr=0.3,0.1

Type RM Length L Ch R = 1 ,20077.4 ,1968.9,1965.5,1962
XS GIS Cut Line= 3
     2153430.115       297503.16     2152707.549       298094.35
     2150237.688      300367.148
#Sta/Elev= 30
       0  2328.2   140.5 2290.57   491.9 2182.38   752.9 2084.92   883.4 2027.71
  1014.2 1986.65    1105 1947.75  1205.7 1926.07  1256.1 1908.11  1286.4 1893.76
  1417.4 1816.53  1538.4 1740.59  1608.9 1706.01  1881.1 1704.74  1981.9 1703.93
  2072.6 1707.77    2133 1715.75  2153.2 1721.55  2213.7 1755.87  2243.9 1768.23
  2405.2 1789.82    2506 1815.01  2717.7 1813.61    2889  1826.9  3080.5 1851.77
  3161.2 1872.45  3403.1 1918.78  3816.3 1985.12  3977.6 2015.54  4290.1 2033.15
#Mann= 3 , 0 , 0
       0      .1       0  1608.9    .045       0  1881.1      .1       0
Bank Sta=1608.9,1881.1
XS Rating Curve= 0 ,0
Exp/Cntr=0.3,0.1