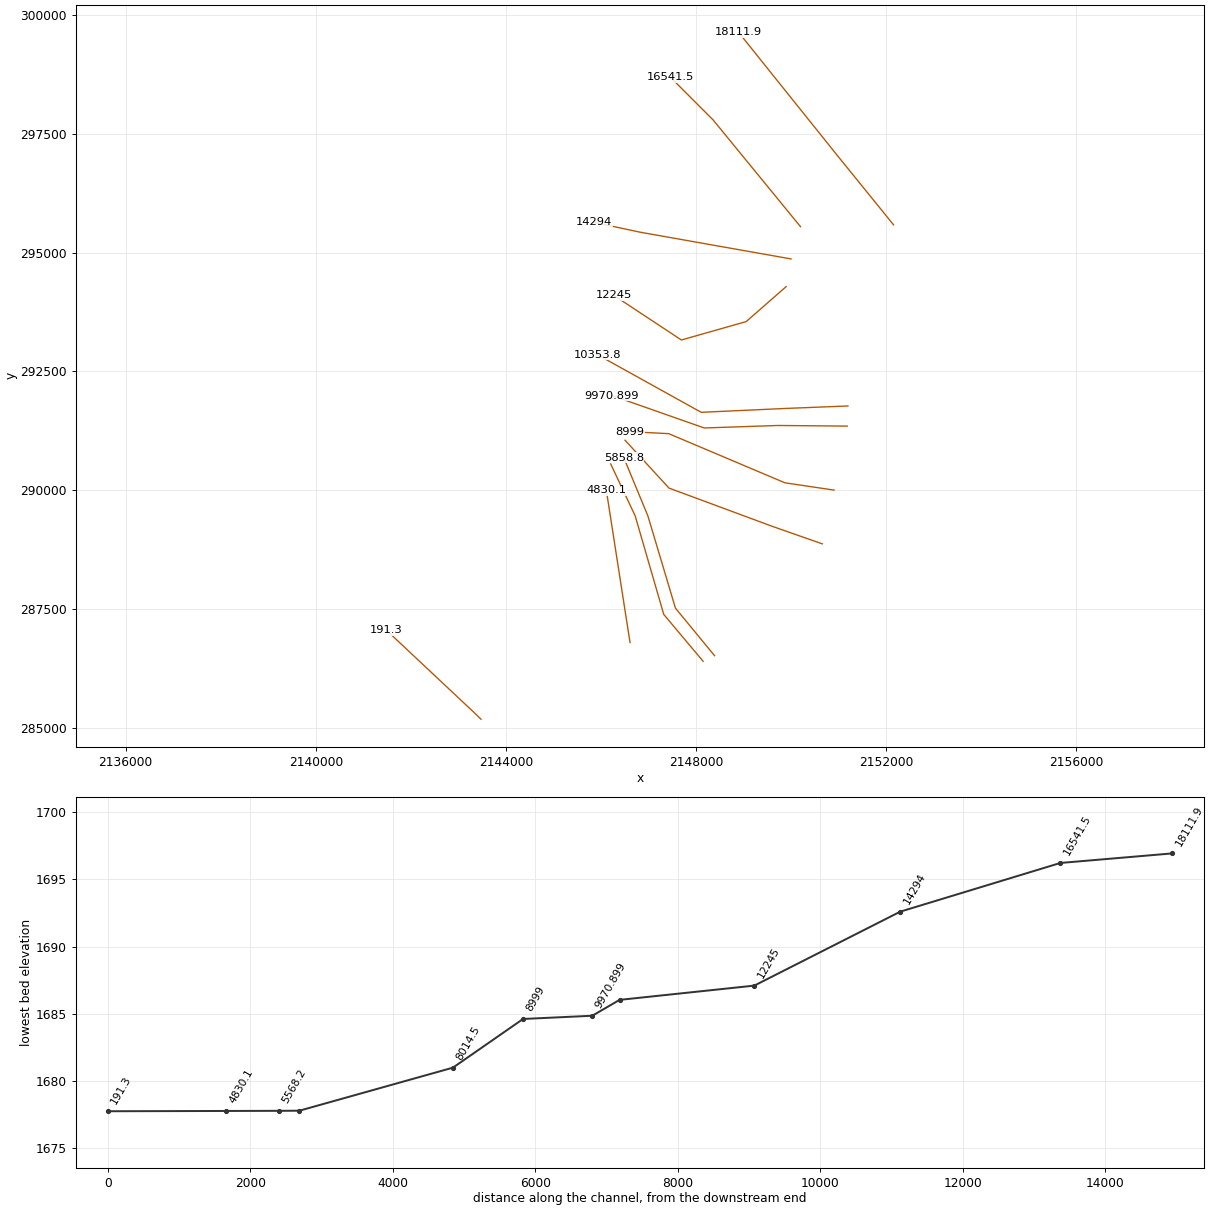
HEC-RAS study GrnbrRv.prj: GrnbrRv

--- GrnbrRv.g01 (geometry) --- (continued)

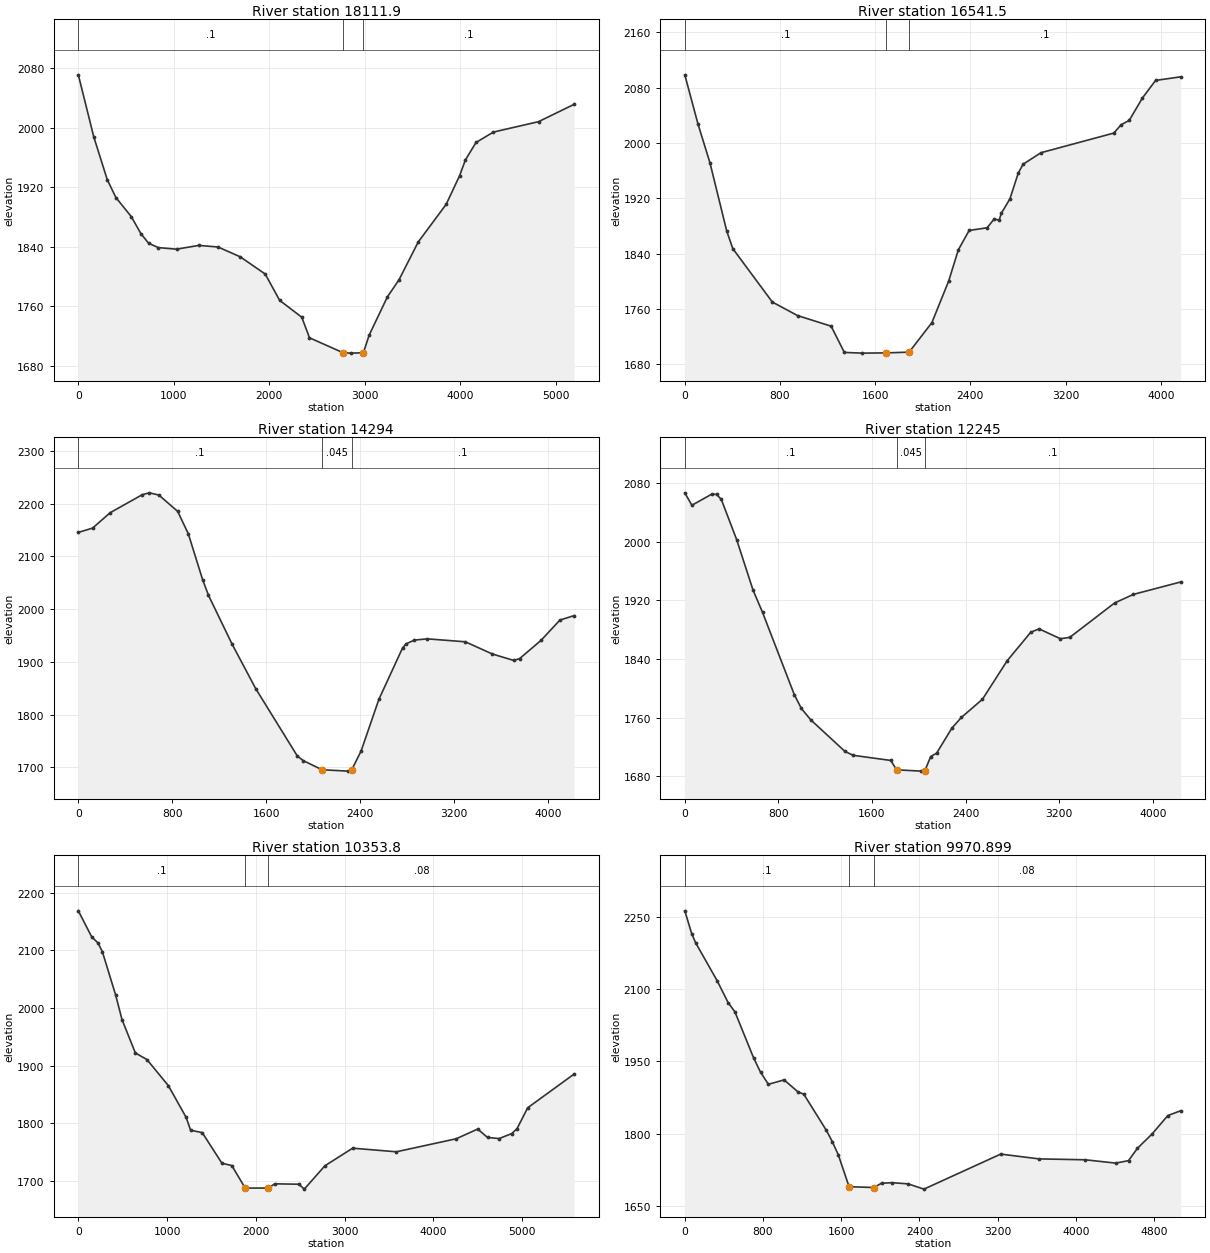
Type RM Length L Ch R = 1 ,18111.9 ,1570.2,1570.4,1570.5
XS GIS Cut Line= 3
     2152155.772      295585.077     2150973.392      297043.346
     2148897.657      299631.445
#Sta/Elev= 30
       0 2070.94   161.5  1987.7   302.8 1930.12   393.6 1906.05   555.1 1880.32
   656.1 1857.38   736.8 1844.53   837.8 1838.76  1029.5 1836.62  1261.7  1841.7
  1463.6 1839.55  1695.7 1826.41  1958.1 1803.22  2109.3 1767.87  2341.2 1745.16
  2421.9 1717.54  2774.9 1697.41  2855.5 1696.93  2986.6  1697.4  3047.1  1721.1
  3238.7 1772.66  3359.8 1795.47  3561.4 1846.33  3853.9  1896.9    3995 1935.47
  4055.6 1956.53  4166.5    1980    4348 1993.97  4821.9 2007.99    5195 2031.34
#Mann= 3 , 0 , 0
       0      .1       0  2774.9    .045       0  2986.6      .1       0
Bank Sta=2774.9,2986.6
XS Rating Curve= 0 ,0
Exp/Cntr=0.3,0.1

Type RM Length L Ch R = 1 ,16541.5 ,2231.7,2247.5,2263.3
XS GIS Cut Line= 3
     2150198.276      295545.664     2148359.018      297792.187
     2147465.664       298685.54
#Sta/Elev= 30
       0  2098.7   110.9  2027.5   211.7 1971.31   352.8 1872.54   403.2 1847.39
   735.9 1770.07   947.6 1750.53  1229.9 1735.18  1340.8 1697.24    1492 1696.22
  1693.6 1696.56  1885.2 1697.66  2076.7 1740.39  2217.9 1800.62  2298.5 1845.51
  2389.3 1873.58  2540.5 1877.52    2601 1890.42  2641.3 1888.42  2661.4 1898.86
    2732 1919.21  2802.6 1956.73  2842.9 1969.42  2993.6 1986.09  3605.3 2014.46
  3665.4 2026.28  3735.6 2032.99  3845.9 2065.21  3956.2  2090.6  4166.8 2095.81
#Mann= 3 , 0 , 0
       0      .1       0  1693.6    .045       0  1885.2      .1       0
Bank Sta=1693.6,1885.2
XS Rating Curve= 0 ,0
Exp/Cntr=0.3,0.1

Type RM Length L Ch R = 1 ,14294   ,2038.7,2049,2059.2
XS GIS Cut Line= 3
      2149998.78      294867.287     2146835.061      295427.426
     2145849.744      295637.627
#Sta/Elev= 30
       0 2145.63   120.9 2153.72   271.9 2183.09   543.9 2217.13   604.3 2220.69
   684.9 2216.53     846 2185.45   936.7 2142.56  1057.6 2056.13  1107.9 2026.19
  1309.3  1933.3  1510.8 1848.74  1863.3 1721.59  1913.6 1712.62  2074.8  1695.2
  2296.4  1692.6  2326.6 1694.79  2407.2 1730.98  2558.2 1828.82  2759.7  1926.3
  2789.9 1934.17  2860.4 1941.24  2971.2  1943.6  3293.5 1938.03  3525.2 1914.78
  3706.6 1902.58    3757 1906.29  3938.3 1940.72  4099.5 1979.32  4220.4 1987.71
#Mann= 3 , 0 , 0
       0      .1       0  2074.8    .045       0  2326.6      .1       0
Bank Sta=2074.8,2326.6
XS Rating Curve= 0 ,0
Exp/Cntr=0.3,0.1

Type RM Length L Ch R = 1 ,12245   ,1898.8,1891.3,1883.6
XS GIS Cut Line= 4
     2149896.112      294284.459     2149055.308      293548.755
       2147691.9      293161.481     2146270.146      294100.533
#Sta/Elev= 30
       0 2066.48    60.4  2049.5   231.5 2064.78   271.8 2064.29     312 2057.52
   442.9 2002.85   583.8 1933.69   664.3 1903.59   936.1 1791.32   996.4 1772.51
    1077 1756.97  1368.5 1714.06  1438.9 1708.66  1760.6 1701.66  1810.8 1688.88
  2021.9  1687.1  2052.1 1687.54  2102.3 1707.04  2152.6 1711.56  2283.3 1745.76
  2363.7 1760.22  2544.7 1785.11  2756.4 1837.72    2958  1876.5  3028.6 1880.98
  3210.1 1867.64  3290.7 1869.41  3673.9 1916.32  3835.2 1928.04  4238.5 1944.95
#Mann= 3 , 0 , 0
       0      .1       0  1810.8    .045       0  2052.1      .1       0
Bank Sta=1810.8,2052.1
XS Rating Curve= 0 ,0
Exp/Cntr=0.3,0.1

Type RM Length L Ch R = 1 ,10353.8 ,382.4,382.9,383.4
XS GIS Cut Line= 4
     2151195.897      291773.518     2149882.141      291720.968
      2148109.27      291639.974     2145927.736      292850.798
#Sta/Elev= 30
       0 2168.79   150.6 2123.59   220.8 2113.24     271  2097.8   421.5 2022.11
   491.8 1980.13   642.4 1922.27   772.8 1910.78  1013.7 1865.62  1214.4 1810.44
  1264.6 1788.21  1395.5 1784.07  1617.3 1730.96  1728.2 1726.97  1879.5 1687.92
  2141.7  1687.9  2212.2 1695.24  2484.5 1694.58    2545 1686.04  2776.9 1726.46
  3089.5 1757.06  3582.5 1750.81  4256.6 1773.42    4498 1790.23  4608.7 1775.71
  4739.5 1773.76  4880.3 1782.32  4940.7 1790.79  5061.4 1827.17  5584.6  1885.7
#Mann= 3 , 0 , 0
       0      .1       0  1879.5    .045       0  2141.7     .08       0
Bank Sta=1879.5,2141.7
XS Rating Curve= 0 ,0
Exp/Cntr=0.3,0.1

Type RM Length L Ch R = 1 ,9970.899,980,971.8,963.6
XS GIS Cut Line= 4
     2151181.926      291349.783     2149723.657       291362.92
     2148173.425       291310.37     2146229.066      291993.523
#Sta/Elev= 30
       0 2262.99    70.4 2215.79   110.6 2196.72   331.9 2117.37   442.5 2072.51
   512.9 2052.99     704 1957.33   774.4 1927.78   854.9 1902.66  1015.8  1911.8
  1156.6 1886.93    1217 1882.06  1448.3 1806.74  1508.7 1783.36  1569.1 1756.48
  1679.9 1689.91  1931.7 1688.22  2012.3 1697.14  2123.1 1698.21  2284.2 1695.78
  2445.4 1684.86  3230.6 1757.64  3622.7 1747.67  4095.2  1745.8  4406.8  1738.9
  4537.5 1744.02    4628 1769.54  4778.8 1799.52  4939.6 1837.73  5070.3 1847.63
#Mann= 3 , 0 , 0
       0      .1       0  1679.9    .045       0  1931.7     .08       0
Bank Sta=1679.9,1931.7
XS Rating Curve= 0 ,0
Exp/Cntr=0.3,0.1

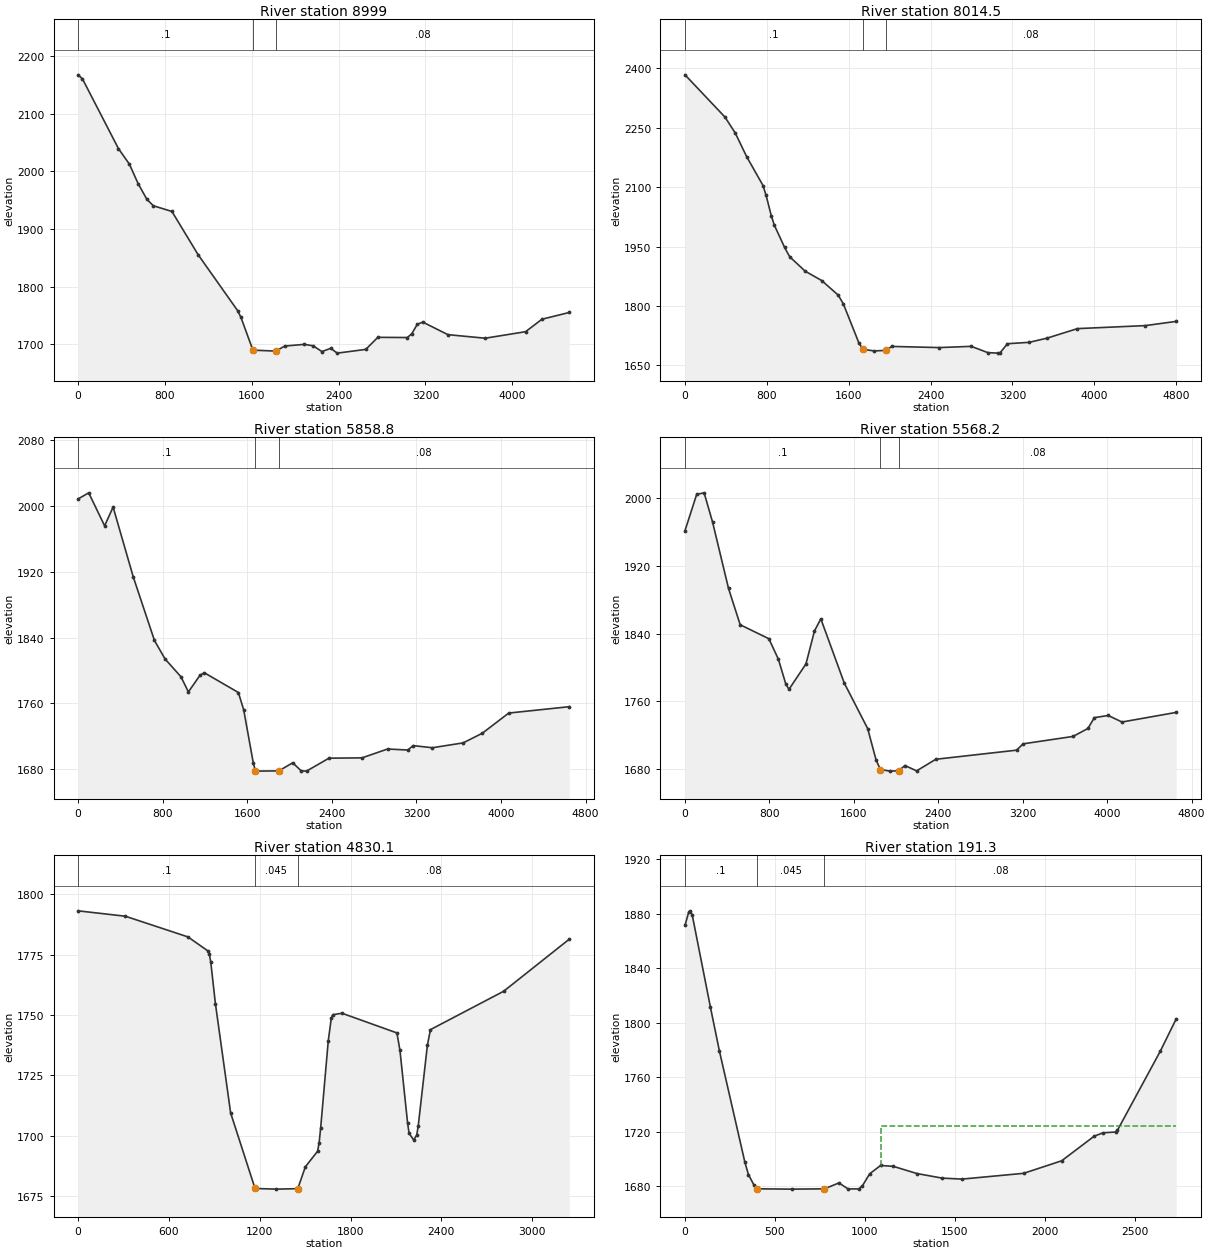
Type RM Length L Ch R = 1 ,8999    ,983.4,984.5,985.6
XS GIS Cut Line= 4
     2150904.279      290003.091     2149870.428      290156.772
     2147425.509      291190.623     2146601.222      291232.536
#Sta/Elev= 30
       0 2167.06    40.2 2160.05   371.8 2039.15   472.4 2012.28   552.8 1978.51
   633.2 1951.39   693.5 1940.06   864.3 1930.22  1105.8 1855.23  1469.1 1758.43
  1499.4 1747.01  1610.4 1689.77  1822.4 1688.16  1903.1 1696.88  2084.8 1699.82
  2165.6 1697.29  2246.3 1687.33    2327 1692.92  2387.6 1684.62    2650 1691.08
  2761.1 1711.98  3033.6 1711.66    3074 1718.23  3124.4 1734.45  3174.9 1738.46
    3407 1716.63  3750.1 1710.48  4122.5 1721.76  4273.4 1743.42  4525.1 1755.11
#Mann= 3 , 0 , 0
       0      .1       0  1610.4    .045       0  1822.4     .08       0
Bank Sta=1610.4,1822.4
XS Rating Curve= 0 ,0
Exp/Cntr=0.3,0.1

Type RM Length L Ch R = 1 ,8014.5  ,2176.8,2155.7,2134.7
XS GIS Cut Line= 4
      2150658.09      288871.785     2149607.086      289239.636
     2147431.306      290045.481     2146506.622      291052.619
#Sta/Elev= 30
       0 2383.46   391.2 2276.62   491.6 2236.36   601.9  2177.2   762.4 2104.08
   792.5 2079.14   842.7 2028.34   872.8 2004.08   973.1 1947.93  1023.2 1924.27
    1174 1887.93  1335.4 1864.32  1496.9 1827.55  1547.3 1805.57  1698.6 1707.26
    1739 1690.55  1849.9 1686.58  1960.9 1687.86  2021.4 1697.92  2485.5    1695
  2798.2  1698.1  2959.6 1682.25  3060.5    1681  3080.7 1682.15  3151.3 1704.75
  3363.1 1708.22  3534.3  1718.5  3835.9 1742.87  4499.4 1750.47    4801  1761.1
#Mann= 3 , 0 , 0
       0      .1       0    1739    .045       0  1960.9     .08       0
Bank Sta=1739,1960.9
XS Rating Curve= 0 ,0
Exp/Cntr=0.3,0.1

Type RM Length L Ch R = 1 ,5858.8  ,290.8,290.6,291.5
XS GIS Cut Line= 4
     2148389.671      286519.747     2147567.351      287518.803
     2146987.117      289459.954     2146480.347      290684.768
#Sta/Elev= 30
       0 2008.29   100.3  2015.7   250.8 1975.63     331 1998.42   521.6 1913.64
   722.2 1836.43   822.5 1813.98     973 1792.34  1043.2 1773.97  1153.5  1794.3
  1193.6 1797.27  1515.7 1773.26  1566.1  1752.3  1656.8 1687.83    1677 1678.26
  1687.1  1677.8  1898.7 1678.09  2029.8 1687.91  2110.4  1678.1  2160.8 1677.84
  2372.5 1693.52    2685  1693.9  2926.9 1704.64  3118.4 1703.44  3168.8 1708.78
  3350.1  1706.2  3641.3 1712.08  3822.1 1723.74  4073.1 1748.31  4645.5 1756.03
#Mann= 3 , 0 , 0
       0      .1       0    1677    .045       0  1898.7     .08       0
Bank Sta=1677,1898.7
XS Rating Curve= 0 ,0
Exp/Cntr=0.3,0.1

Type RM Length L Ch R = 1 ,5568.2  ,741,738,733.9
XS GIS Cut Line= 4
     2148148.817      286401.924     2147321.151      287387.241
     2146720.012      289459.954     2146204.458      290553.392
#Sta/Elev= 30
       0 1961.68   110.6 2004.46     181 2006.22   261.4 1971.51   412.2 1893.35
   522.8 1850.52   794.2 1834.06   884.7 1809.85     955 1780.52   985.2 1774.38
  1146.1 1804.34  1226.5 1843.22  1286.8 1857.51  1508.7 1781.79  1730.5 1728.03
  1811.2  1690.5  1851.6 1679.68  1942.3 1677.79    2023 1678.14  2083.5  1684.4
  2194.4 1678.09    2376 1691.78  3142.4 1702.54  3202.9 1709.99  3676.6 1718.74
  3817.7 1728.17  3878.1 1740.89  4009.1 1743.48    4140 1735.75  4653.8  1747.1
#Mann= 3 , 0 , 0
       0      .1       0  1851.6    .045       0    2023     .08       0
Bank Sta=1851.6,2023
XS Rating Curve= 0 ,0
Exp/Cntr=0.3,0.1

Type RM Length L Ch R = 1 ,4830.1  ,1658.9,1661.5,1664.1
XS GIS Cut Line= 3
      2146611.34      286795.881     2146507.496      287463.194
     2146112.269      290002.962
#Sta/Elev= 30
       0 1793.16   312.5 1790.92   725.7 1782.35   856.8 1776.58   866.9 1775.42
   876.9 1771.75   907.2 1754.73    1008 1709.35  1169.2 1678.05  1310.4 1677.78
  1451.5 1677.97  1501.9 1687.05  1582.5 1693.48  1592.6 1696.98  1602.7 1703.03
  1653.1 1739.32  1673.2 1748.63  1683.3 1750.08  1743.8  1750.7  2106.7 1742.54
  2126.8 1735.31  2177.2 1705.21  2187.3 1700.88  2217.6 1698.17  2237.7 1700.16
  2247.8 1704.13  2308.3 1737.54  2328.4 1743.91  2812.2 1759.82  3245.7 1781.41
#Mann= 3 , 0 , 0
       0      .1       0  1169.2    .045       0  1451.5     .08       0
Bank Sta=1169.2,1451.5
XS Rating Curve= 0 ,0
Exp/Cntr=0.3,0.1

Type RM Length L Ch R = 1 ,191.3   ,189.7,191.3,192.8
XS GIS Cut Line= 4
     2143475.589      285182.421     2143331.103      285322.874
     2141825.922      286736.005      2141486.42      287054.745
#Sta/Elev= 30
       0 1871.44    20.2 1881.12    30.2 1882.15    40.3    1879     141 1811.56
   191.4 1779.12   332.4 1697.83   352.6 1688.49   382.8 1680.91   402.9 1677.99
   594.3 1677.76   775.6 1677.97   856.1 1682.32   906.5 1677.92   966.9 1677.92
     987  1680.3  1027.3 1689.06  1087.8 1695.13  1158.3 1694.51  1289.2 1689.22
  1430.2 1685.84    1541 1685.13  1883.4 1689.37  2094.9 1698.58    2276 1716.67
  2325.5 1719.16  2394.9 1719.69  2404.8 1720.92  2642.6  1778.9  2731.8 1802.77
#Mann= 3 , 0 , 0
       0      .1       0   402.9    .045       0   775.6     .08       0
#XS Ineff= 2 , 0
                         1091.81          1724.1
Permanent Ineff=
       F       F
Bank Sta=402.9,775.6
XS Rating Curve= 0 ,0
Exp/Cntr=0.3,0.1
Stream Node=GrnbrRv         ,Main            , 0 , 0 ,Upstream end
Stream Node=GrnbrRv         ,Main            , 0 , 1 ,Downstream end

Chan Stop Cuts=-1
Use User Specified Reach Order=0
Composite Channel Slope=5